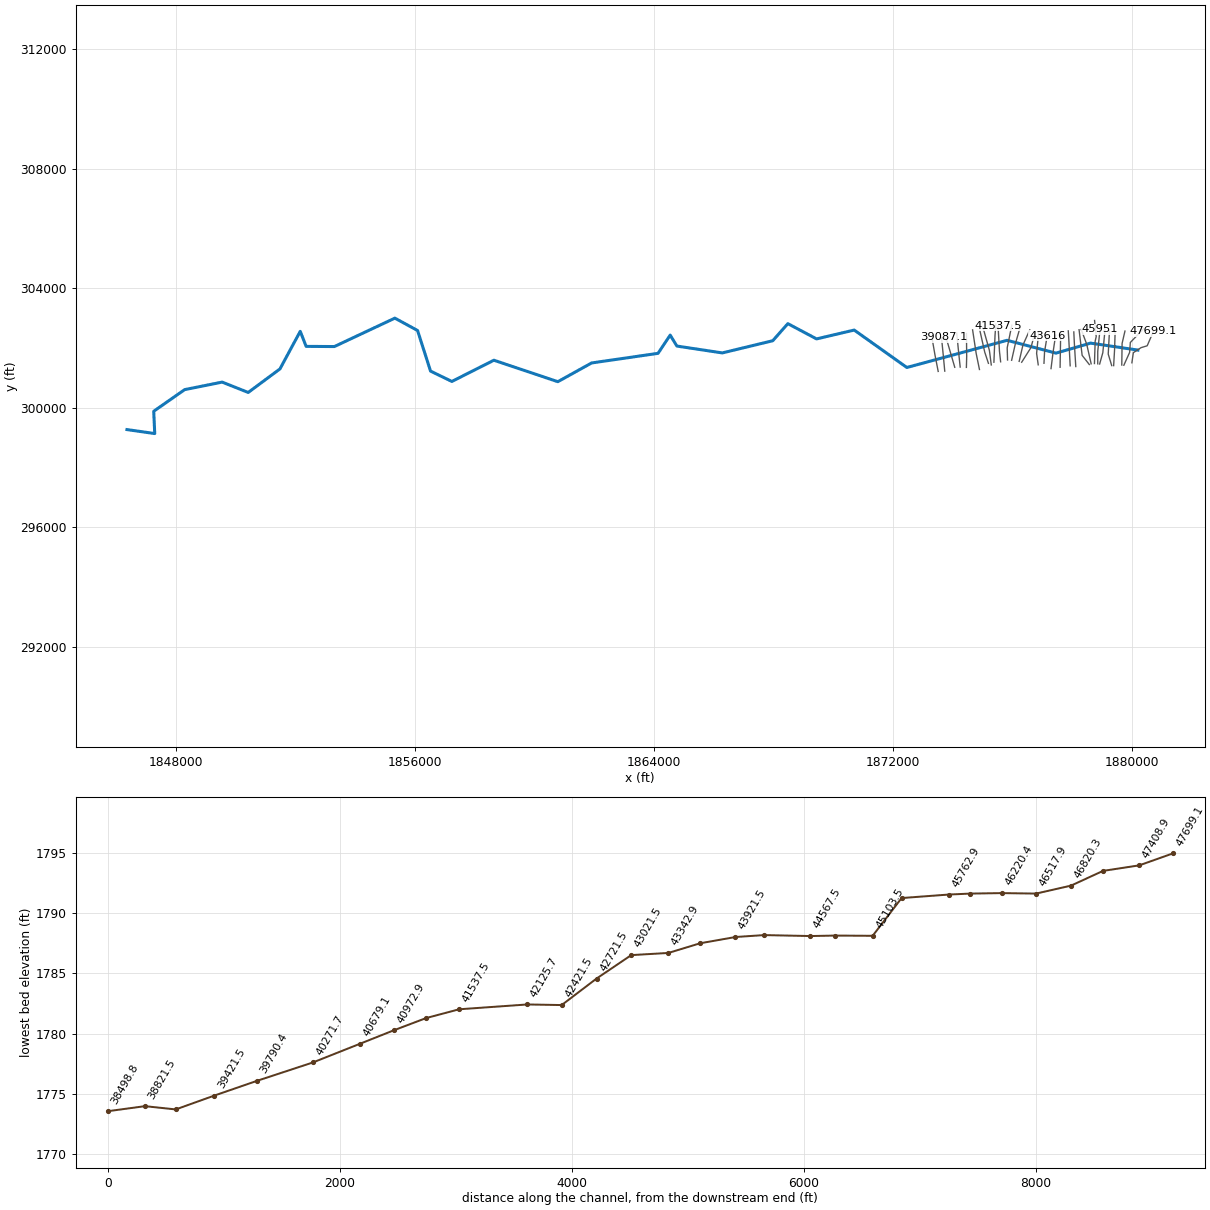
--- SndlckCrk.prj (project) ---

Proj Title=SndlckCrk
Current Plan=p01
Default Exp/Contr=0,0
English Units
Geom File=g01
Flow File=f01
Plan File=p01
BEGIN DESCRIPTION:
END DESCRIPTION:
DSS Export Rating Curves= 0
DSS Export Rating Curve Sorted= 0
DSS Export Volume Flow Curves= 0
DXF OffsetX= 0
DXF OffsetY= 0
DXF ScaleX= 0
DXF ScaleY= 0

--- SndlckCrk.p01 (plan) ---

Plan Title=Floodplain
Program Version=4.00
Geom File=g01
Flow File=f01
K Sum by GR=0
Std Step Tol=0.01
Critical Tol=0.01
Num of Std Step Trials=20
Max Error Tol=0.3
Flow Tol Ratio=0.001
Split Flow NTrial=30
Split Flow Tol=0.02
Split Flow Ratio=0.02
Log Output Level=0
Friction Slope Method=1
Unsteady Friction Slope Method=2
Unsteady Bridges Friction Slope Method=1
Global Log Level=0
CheckData=False
Run HTab=0
Run UNet=0
Run PostProcess=0
UNET Theta=0
UNET Theta Warmup=0
UNET ZTol=0
UNET ZSATol=0
UNET MxIter=0
UNET MaxInSteps=0
UNET DtIC=0
UNET DtMin=0
UNET MaxCRTS=0
UNET WFStab=0
UNET SFStab=0
UNET WFX=0
UNET SFX=0
UNET DSS MLevel=0
UNET DZMax Abort=0
UNET Convert EG Bridges=0
UNET Use Existing IB Tables=0
UNET Froude Limit=0
UNET Froude Power=0
Write IC File=0
Echo Input=False
Echo Output=False
Write Detailed=0

--- SndlckCrk.f01 (steady flow) ---

Flow Title=NFF Regression Equation
Program Version=4.00
Number of Profiles=1
Profile Names=P100yr
River Rch & RM=SndlckCrk,Main      ,47699.1
715.5125
River Rch & RM=SndlckCrk,Main      ,47408.9
897.6510
River Rch & RM=SndlckCrk,Main      ,45355.5
938.9210
River Rch & RM=SndlckCrk,Main      ,45103.5
1035.703
River Rch & RM=SndlckCrk,Main      ,40972.9
1109.536
River Rch & RM=SndlckCrk,Main      ,40679.1
1270.785
River Rch & RM=SndlckCrk,Main      ,37123.2
1345.312
River Rch & RM=SndlckCrk,Main      ,36731.4
1869.774
River Rch & RM=SndlckCrk,Main      ,33987.5
2067.527
River Rch & RM=SndlckCrk,Main      ,32185
2296.418
River Rch & RM=SndlckCrk,Main      ,23466.8
2474.759
River Rch & RM=SndlckCrk,Main      ,23188
2798.688
River Rch & RM=SndlckCrk,Main      ,21546.1
2824.424
River Rch & RM=SndlckCrk,Main      ,20900.4
3548.307
River Rch & RM=SndlckCrk,Main      ,13373.7
3866.515
River Rch & RM=SndlckCrk,Main      ,243.7
4230.441
Boundary for River Rch & Prof#=SndlckCrk,Main      ,1
Up Type=0
Dn Type=3
Dn Slope=0.011958

--- SndlckCrk.g01 (geometry) ---

Geom Title=USGS 3m DEM
Program Version=4.10

River Reach=SndlckCrk       ,Main
Reach XY= 30
     1880199.763      301933.165     1878615.955      302166.214
     1877458.268        301831.5     1875822.315      302260.073
     1872465.697      301351.008     1870703.425      302602.779
      1869442.58      302307.144     1868481.337      302817.759
     1867975.943      302245.969     1866286.566      301838.332
     1864766.536      302067.621     1864542.253      302433.904
     1864136.111       301824.07     1861912.341      301502.696
       1860780.8      300875.943     1858639.875      301593.826
     1857232.749      300883.874     1856519.484      301229.594
     1856083.988      302588.903     1855324.636      303001.825
     1853299.197      302051.059     1852353.573      302057.604
     1852156.911       302560.38     1851478.204       301303.52
     1850415.381      300515.496      1849542.71      300861.995
     1848287.882      300610.291     1847252.134      299886.646
     1847285.395      299140.156     1846356.745      299272.949

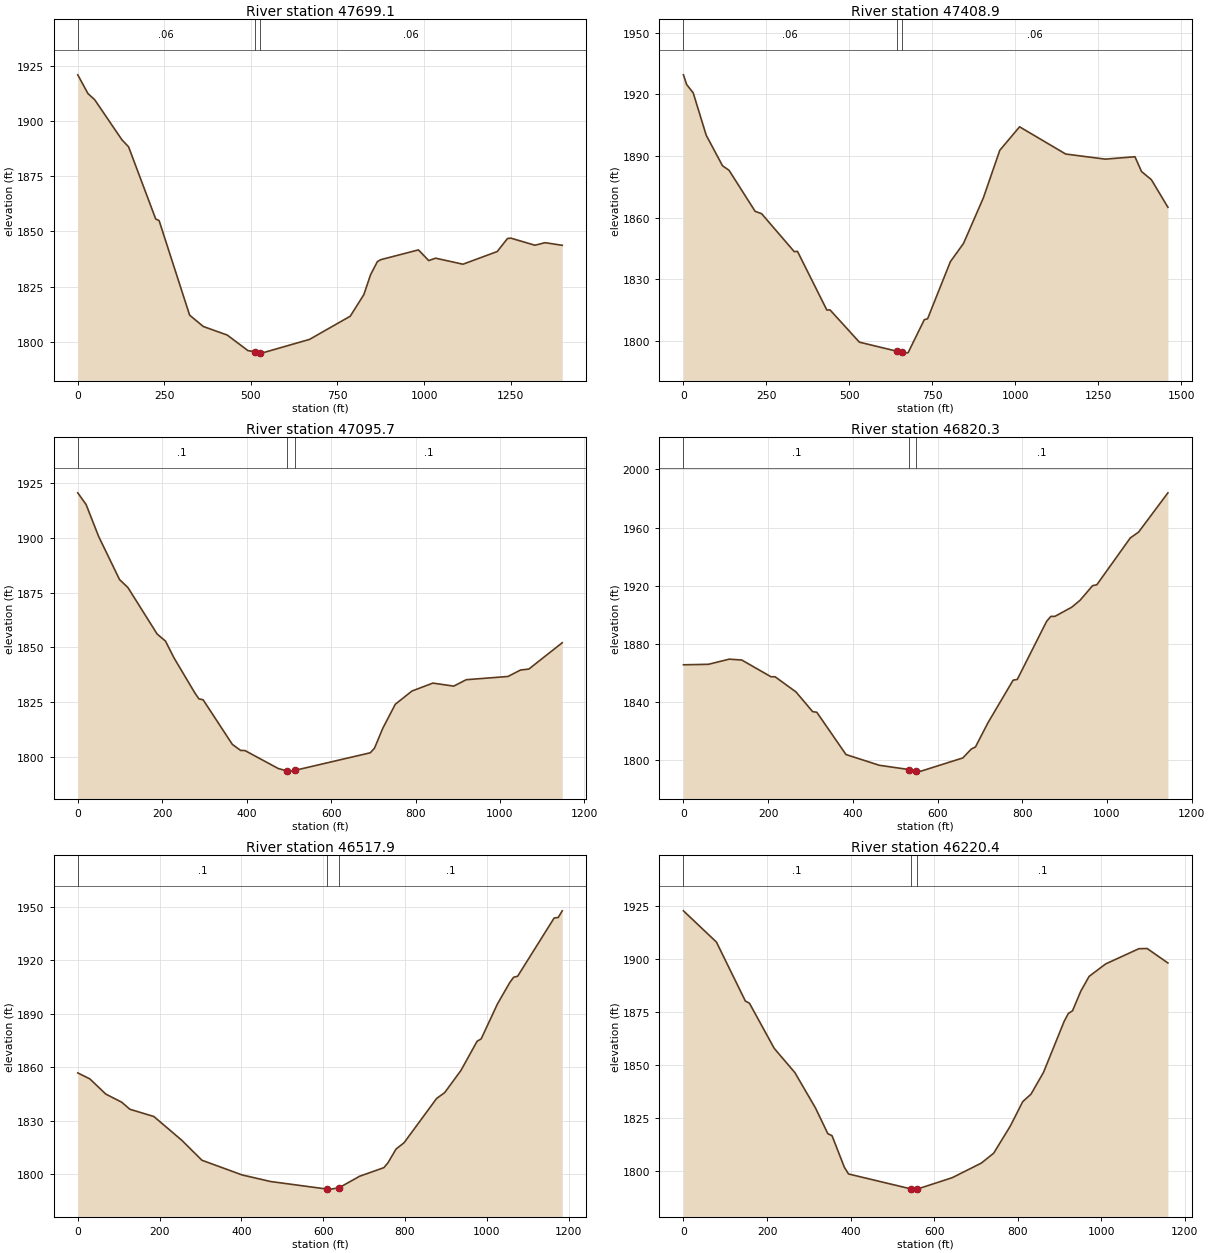
Type RM Length L Ch R = 1 ,47699.1 ,269,289.9,310.8
XS GIS Cut Line= 5
     1879999.168      301507.933     1880048.182      301846.996
     1880305.771      302014.429     1880511.676      302077.554
     1880723.593      302567.518
#Sta/Elev= 30
       0 1920.81    29.4 1912.34    48.9 1909.55   127.2  1891.5   146.8 1888.23
   225.1  1855.6   234.9 1854.88     323 1812.12   362.4 1806.99   431.8 1803.09
   491.2 1796.09   511.3  1795.5   526.3 1795.01   530.9 1794.93   669.4 1801.15
   786.9 1811.64     826 1821.37   845.6 1830.43   865.2 1836.33   875.1 1837.21
   983.8 1841.62  1013.5 1836.78  1033.2 1837.88  1112.3 1835.15  1211.2 1840.88
  1240.8 1846.77  1250.7 1846.94  1319.9 1843.74  1349.6 1844.88    1399  1843.7
#Mann= 3 , 0 , 0
       0     .06       0   511.3    .045       0   526.3     .06       0
Bank Sta=511.3,526.3
XS Rating Curve= 0 ,0
Exp/Cntr=0.3,0.1

Type RM Length L Ch R = 1 ,47408.9 ,311.5,312.5,314.8
XS GIS Cut Line= 4
     1879730.446       301426.98      1879924.02      301856.619
     1879947.208      302188.623     1880403.463      302659.198
#Sta/Elev= 30
       0 1929.57     9.8 1924.83    29.4 1920.79    68.7 1900.11   117.8 1885.25
   137.4 1883.05     216 1863.05   235.6 1861.89   333.8 1843.41   343.6 1843.53
     432 1814.96   441.8 1814.98     530 1799.29   643.2 1794.86   658.2 1794.29
     667 1793.94   676.8 1794.16   725.7 1810.26   735.5 1810.68     804 1838.46
   843.8 1847.44   903.4 1869.56     953 1892.78  1012.6 1904.24  1151.6 1890.97
  1270.8 1888.48  1360.2 1889.65    1380 1882.44  1409.8 1878.45  1459.5 1865.01
#Mann= 3 , 0 , 0
       0     .06       0   643.2    .045       0   658.2     .06       0
Bank Sta=643.2,658.2
XS Rating Curve= 0 ,0
Exp/Cntr=0.3,0.1

Type RM Length L Ch R = 1 ,47095.7 ,285.7,275.3,275.4
XS GIS Cut Line= 3
     1879660.682      301433.434     1879671.523      302155.707
     1879767.364      302569.763
#Sta/Elev= 30
       0 1920.49    19.8 1915.13    49.5 1900.56      99 1880.89   118.7 1877.29
     188 1856.05   207.8 1852.82   227.6 1845.28   277.1 1829.23     287 1826.45
   296.9 1826.04   366.1 1805.68   385.9 1802.91   395.8 1802.89     475 1794.66
   494.8 1793.62   504.7 1793.48   514.6 1793.85   692.7 1801.85   702.6  1803.9
   722.4 1813.04     752    1824   791.5 1830.04     841 1833.65   890.4 1832.28
     920  1835.2  1018.9 1836.68  1048.5 1839.62  1068.3 1840.06  1147.4 1852.08
#Mann= 3 , 0 , 0
       0      .1       0   494.8    .045       0   514.6      .1       0
Bank Sta=494.8,514.6
XS Rating Curve= 0 ,0
Exp/Cntr=0.3,0.1

Type RM Length L Ch R = 1 ,46820.3 ,301.5,301.6,301
XS GIS Cut Line= 3
     1879388.753      301413.134     1879419.613      301953.446
     1879439.061      302555.739
#Sta/Elev= 30
       0 1865.48      59 1865.82   108.2 1869.37   137.8 1868.76   206.6 1857.26
   216.5 1857.22   265.7  1846.8     305 1833.25   314.9 1832.79   383.8 1803.68
   462.5 1796.29   533.7  1793.3   548.7 1792.65     561 1792.26   659.7 1801.35
   679.5 1807.47   689.4 1808.89     719 1825.59   778.3 1854.88   788.2 1855.42
   857.3 1895.34   867.2 1898.78   877.1 1898.84   916.6 1905.12   936.3 1909.89
     966 1919.99   975.9 1920.57  1054.9  1952.8  1074.6 1956.88  1143.8  1983.9
#Mann= 3 , 0 , 0
       0      .1       0   533.7    .045       0   548.7      .1       0
Bank Sta=533.7,548.7
XS Rating Curve= 0 ,0
Exp/Cntr=0.3,0.1

Type RM Length L Ch R = 1 ,46517.9 ,293.4,296.9,276.2
XS GIS Cut Line= 3
     1879323.931      301413.945     1879207.109      301798.003
     1879248.942      302579.792
#Sta/Elev= 30
       0 1856.76    29.4 1853.43    68.5 1844.89   107.7  1840.3   127.3 1836.39
     186 1832.32   254.6 1818.93   303.5  1807.8   401.4 1799.58   470.8 1795.89
   609.6 1791.61   619.5  1791.6   639.3 1792.44   688.8  1798.8   748.3 1803.65
   758.2 1806.34     778 1814.05   797.8 1817.66   877.1 1842.41   896.9 1845.71
   936.6 1858.13   976.2 1874.52   986.1 1875.84  1025.8 1895.38  1055.5 1907.22
  1065.4 1910.38  1075.3 1910.98  1164.5 1943.61  1174.4  1943.9  1184.3 1947.63
#Mann= 3 , 0 , 0
       0      .1       0   609.6    .045       0   639.3      .1       0
Bank Sta=609.6,639.3
XS Rating Curve= 0 ,0
Exp/Cntr=0.3,0.1

Type RM Length L Ch R = 1 ,46220.4 ,258.7,268.5,287.5
XS GIS Cut Line= 3
     1878920.328      301467.792     1879026.504      301848.353
     1879099.453      302609.254
#Sta/Elev= 30
       0 1922.67      79 1907.96   148.2  1880.2     158 1879.17   217.3 1857.91
   266.7 1846.51   316.1 1829.82   345.7 1817.72   355.6 1816.81   385.2 1801.92
   395.1 1798.78   544.2 1791.76   553.9 1791.64   559.2 1791.64   643.3 1797.03
   712.8 1803.88   742.5 1808.56   782.2 1821.31     812 1832.83   831.9 1836.38
   861.7  1846.6   911.3 1870.69   921.2 1874.35   931.2 1875.61     951 1884.85
   970.9 1891.81  1010.6 1897.68    1090 1904.84  1109.8 1904.92  1159.5 1898.11
#Mann= 3 , 0 , 0
       0      .1       0   544.2    .045       0   559.2      .1       0
Bank Sta=544.2,559.2
XS Rating Curve= 0 ,0
Exp/Cntr=0.3,0.1

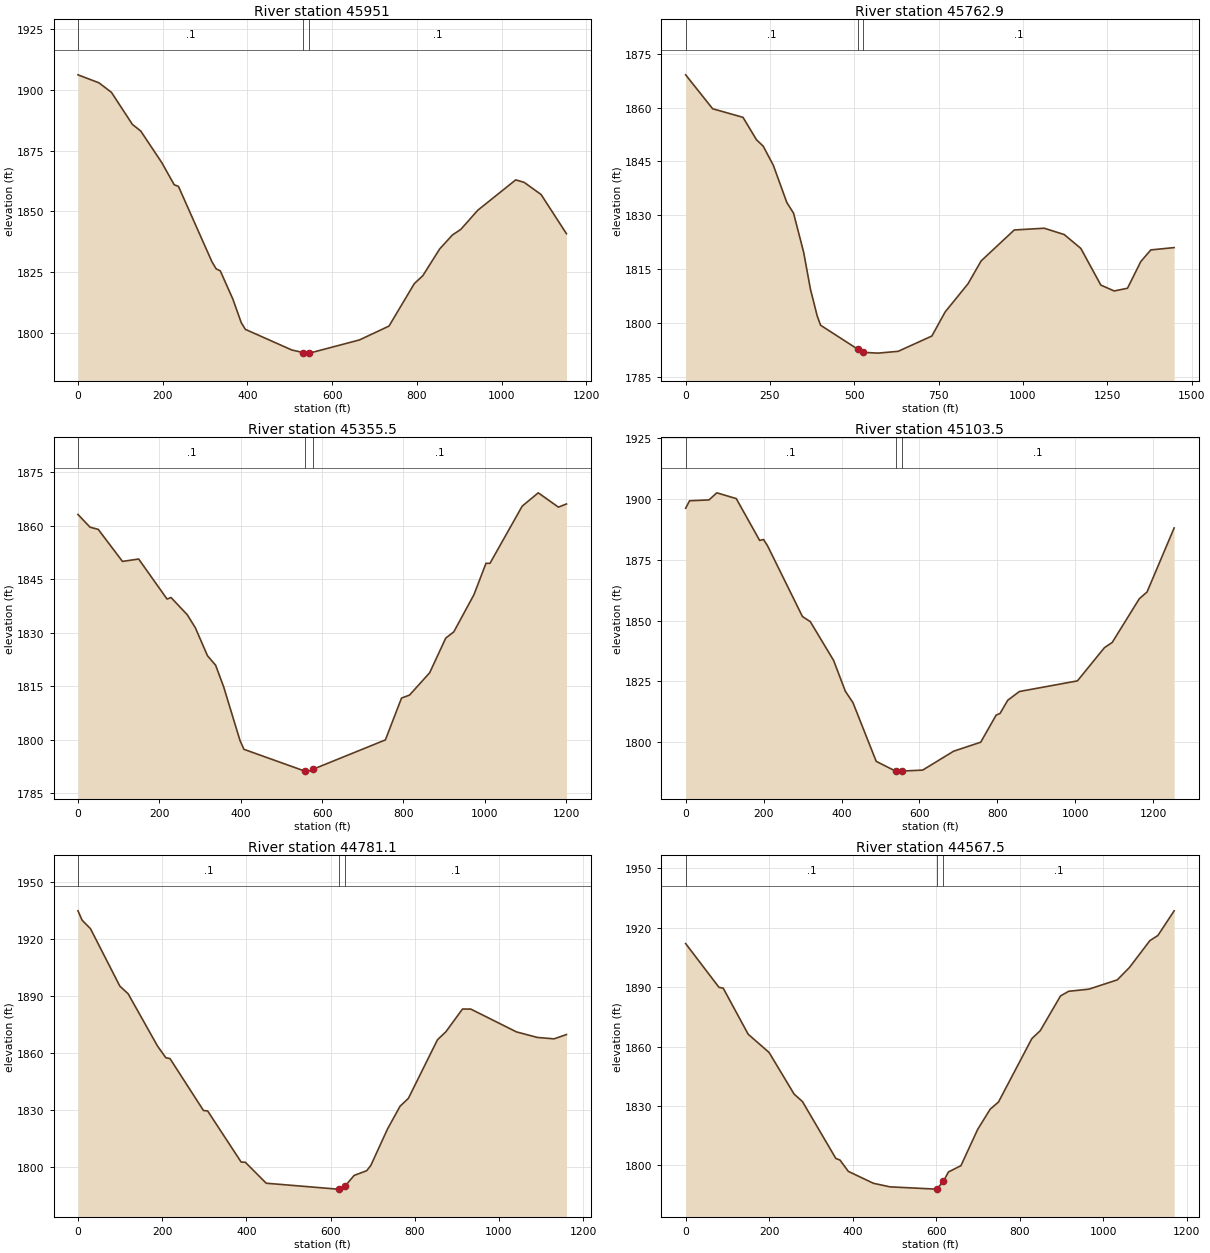
Type RM Length L Ch R = 1 ,45951   ,148.9,187.2,185
XS GIS Cut Line= 3
     1878856.142      301473.456     1878856.169      301888.431
     1878931.789      302622.324
#Sta/Elev= 30
       0 1906.28    49.4    1903      79 1899.06   128.4 1885.87   148.2 1883.11
   197.6 1870.16   227.2 1860.97   237.1 1860.32   316.2 1829.25     326 1826.36
   335.9 1825.49   365.6 1813.84   385.3 1804.16   395.2 1801.38   504.7 1792.89
   531.3 1791.83   544.6  1791.6   546.3  1791.6   664.2 1797.03     734 1802.74
   793.8 1820.26   813.8 1823.49   853.6 1834.53   883.6 1840.27   903.5 1842.59
   943.4 1850.46  1033.1    1863    1053 1861.97  1092.9 1856.96  1152.8 1840.82
#Mann= 3 , 0 , 0
       0      .1       0   531.3    .045       0   546.3      .1       0
Bank Sta=531.3,546.3
XS Rating Curve= 0 ,0
Exp/Cntr=0.3,0.1

Type RM Length L Ch R = 1 ,45762.9 ,397.8,406.2,405
XS GIS Cut Line= 4
     1878745.952      301483.635     1878769.999       302233.11
     1878805.207       302384.21      1878749.96       302924.47
#Sta/Elev= 30
       0 1869.15      80 1859.69     170 1857.29     210 1851.04     230 1849.24
     260 1843.91   299.9 1833.55   319.9 1830.55   349.9 1819.64   369.9 1809.38
   389.9 1801.93   399.9 1799.31     510 1792.63     525 1791.75   569.9 1791.52
   629.9 1792.02   729.9 1796.29   769.2    1803   837.1 1810.87   875.9 1817.24
   974.1 1825.87    1063 1826.36  1122.2  1824.6  1171.6 1820.72  1230.8  1810.5
  1270.4 1808.86  1309.8 1809.62  1349.3 1817.07    1379 1820.31  1448.1 1820.96
#Mann= 3 , 0 , 0
       0      .1       0     510    .045       0     525      .1       0
Bank Sta=510,525
XS Rating Curve= 0 ,0
Exp/Cntr=0.3,0.1

Type RM Length L Ch R = 1 ,45355.5 ,258.7,249.5,236.7
XS GIS Cut Line= 3
     1878635.524      301473.954     1878485.624      302133.676
     1878301.762      302624.377
#Sta/Elev= 30
       0 1863.16    29.8 1859.58    49.8 1858.98   109.4    1850   149.2 1850.67
   218.9 1839.46   228.8 1839.87   268.6 1835.06   288.5 1831.41   318.4 1823.55
   338.3 1820.92   358.2 1814.82     398 1799.89   407.9 1797.34   557.2 1791.25
   567.1 1791.23     577 1791.72   755.6 1799.98   795.2  1811.7     815 1812.55
   864.4  1818.8   903.9 1828.51   923.7 1830.26   973.2 1840.68  1002.8 1849.46
  1012.7 1849.48  1091.8 1865.49  1131.3 1869.22  1180.8 1865.21  1200.6  1866.1
#Mann= 3 , 0 , 0
       0      .1       0   557.2    .045       0     577      .1       0
Bank Sta=557.2,577
XS Rating Curve= 0 ,0
Exp/Cntr=0.3,0.1

Type RM Length L Ch R = 1 ,45103.5 ,318.4,323.3,329
XS GIS Cut Line= 3
     1878573.984      301449.778     1878333.938      301756.824
     1878231.318      302614.438
#Sta/Elev= 30
       0 1896.17      10 1899.24      60  1899.6      80 1902.51   129.9 1900.14
   189.9 1882.94   199.9 1883.32   209.9 1880.82   299.8 1851.64   319.8 1849.58
   379.8 1833.58   409.6 1821.01   429.4 1816.23     489 1792.13   538.7  1788.1
   540.8 1788.11   555.8 1788.13   608.2 1788.52   687.6 1796.29   757.1 1799.98
   796.8 1811.14   806.7  1811.8   826.6 1817.25   856.4 1820.83  1005.3  1825.2
  1074.8 1838.88  1094.6    1841  1164.1 1858.97    1184 1861.74  1253.5 1888.08
#Mann= 3 , 0 , 0
       0      .1       0   540.8    .045       0   555.8      .1       0
Bank Sta=540.8,555.8
XS Rating Curve= 0 ,0
Exp/Cntr=0.3,0.1

Type RM Length L Ch R = 1 ,44781.1 ,214.1,213.1,212
XS GIS Cut Line= 3
     1878120.998      301381.865     1878074.944      302125.769
      1878055.02      302540.261
#Sta/Elev= 30
       0 1934.79     9.9 1929.84    29.8 1925.36    99.4 1895.14   119.2 1891.07
   188.8 1863.58   208.7 1857.38   218.6 1856.92   298.1 1829.56   308.1 1829.31
   387.6 1802.39   397.5 1802.28   447.2 1791.23   616.1 1788.12   619.3 1788.18
   634.3 1789.67   655.9 1795.33   685.7 1797.82   695.6  1800.6   735.4 1819.88
   765.1 1831.82   784.8 1835.95     854 1866.88   873.8 1871.03   913.3 1883.03
     933 1883.01  1041.7 1870.97  1091.1 1868.07  1130.7 1867.31  1160.3 1869.59
#Mann= 3 , 0 , 0
       0      .1       0   619.3    .045       0   634.3      .1       0
Bank Sta=619.3,634.3
XS Rating Curve= 0 ,0
Exp/Cntr=0.3,0.1

Type RM Length L Ch R = 1 ,44567.5 ,401,399.5,397.6
XS GIS Cut Line= 3
     1877933.229      301407.425     1877889.249      302255.266
     1877869.702      302575.345
#Sta/Elev= 30
       0 1911.92    79.9 1889.83    89.9 1889.45   149.8 1866.18   199.8 1857.01
   259.7 1836.01   279.7 1832.25   359.6 1803.57   369.6 1802.73   389.5 1797.04
   449.5 1791.03   489.4 1789.23   599.3 1788.08   602.1 1788.33   617.1 1791.97
   629.2 1796.73   659.2 1799.91   699.2 1818.17   729.1 1828.36   749.1 1832.01
     829    1864     849 1867.96   897.6  1885.5     917 1887.84   965.6 1888.93
  1033.6 1893.62  1062.8 1899.88  1111.4 1913.36  1130.8    1916  1169.7 1928.43
#Mann= 3 , 0 , 0
       0      .1       0   602.1    .045       0   617.1      .1       0
Bank Sta=602.1,617.1
XS Rating Curve= 0 ,0
Exp/Cntr=0.3,0.1

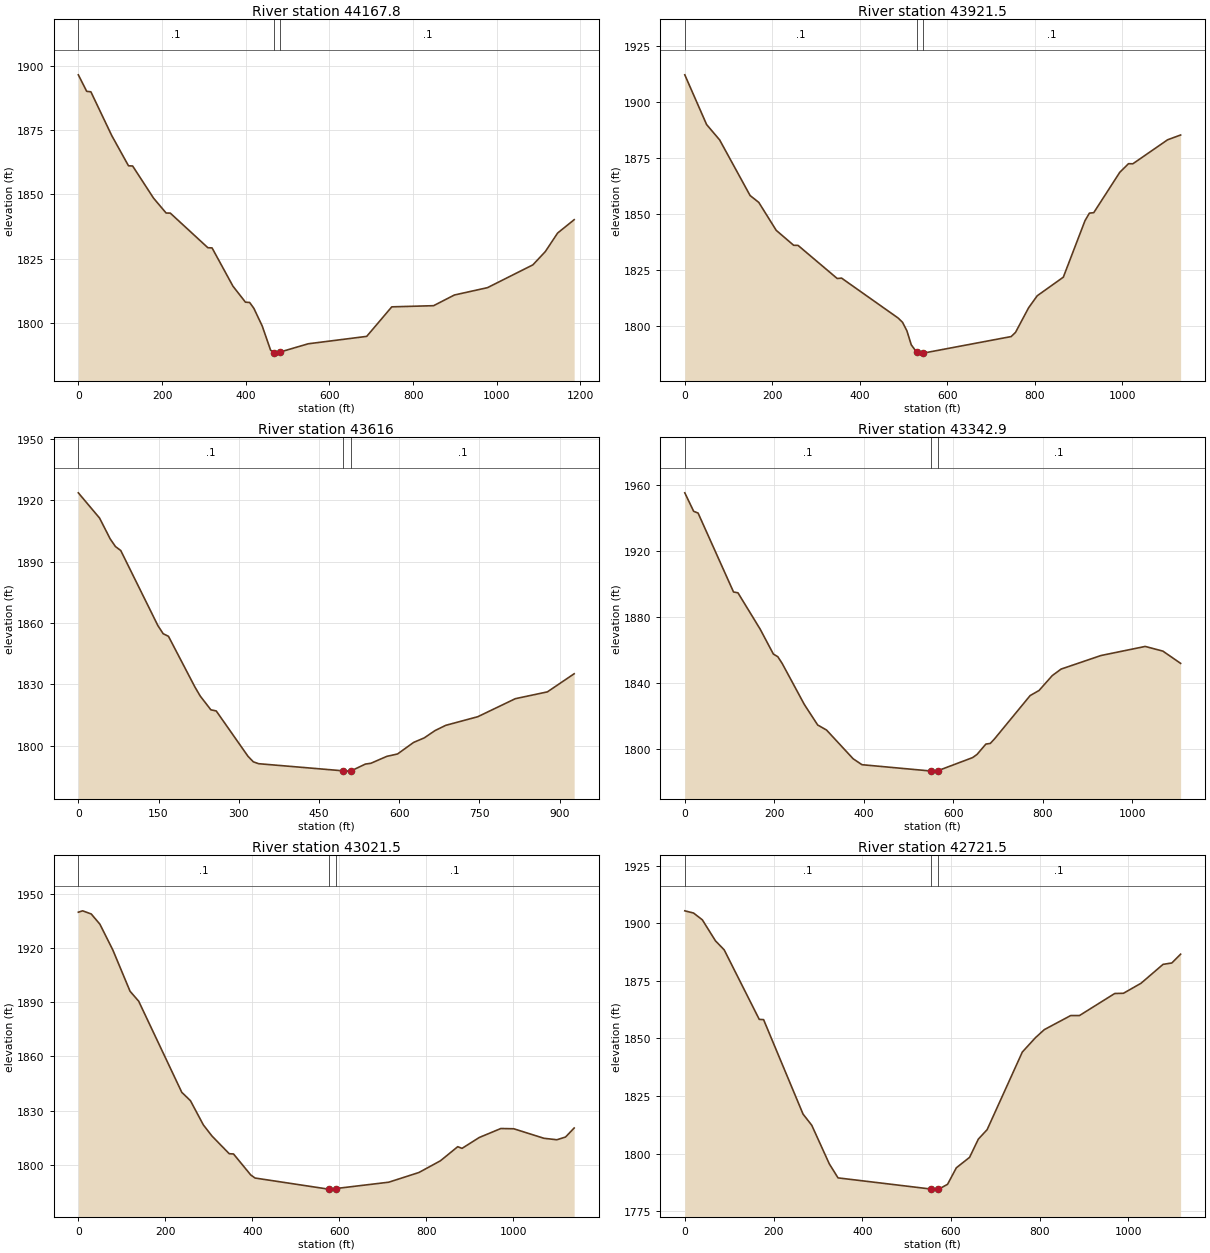
Type RM Length L Ch R = 1 ,44167.8 ,248.7,246.3,243.4
XS GIS Cut Line= 3
     1877595.984      301359.073     1877610.708      302247.936
     1877625.368      302543.581
#Sta/Elev= 30
       0 1896.65      20 1890.22      30 1890.03    79.9 1872.96   119.9 1861.19
   129.8 1861.11   179.8 1848.57   209.8 1842.78   219.8 1842.74   309.6 1829.25
   319.6 1829.18   369.6 1814.24   399.5 1808.02   409.5  1807.9   419.5 1805.63
   439.5 1798.73   459.5 1789.32   467.9 1788.35   469.5 1788.16   482.9 1788.62
   549.4  1791.8   689.2 1794.69   749.1  1806.2     849 1806.65   898.8 1810.82
   977.8 1813.68  1086.3 1822.56  1115.9 1827.71  1145.5 1834.97    1185 1840.17
#Mann= 3 , 0 , 0
       0      .1       0   467.9    .045       0   482.9      .1       0
Bank Sta=467.9,482.9
XS Rating Curve= 0 ,0
Exp/Cntr=0.3,0.1

Type RM Length L Ch R = 1 ,43921.5 ,306,305.3,305.2
XS GIS Cut Line= 3
     1877292.064      301313.444     1877358.716      301846.552
     1877446.113       302435.64
#Sta/Elev= 30
       0 1912.14    49.8 1889.97    79.6 1883.11   149.2  1858.3   169.1 1855.22
   208.9 1842.77   248.7 1836.11   258.7 1836.06   348.2 1821.29   358.2 1821.46
   487.5 1803.64   497.5 1801.74   507.4 1797.96   517.4 1791.72   529.8 1788.39
   537.3    1788   544.8    1788   745.7 1795.39   755.6 1797.26   785.4  1808.2
   805.2 1813.59   864.8 1821.88   914.4 1847.11   924.4 1850.45   934.3 1850.65
   993.8 1868.66  1013.7  1872.5  1023.6 1872.45    1103 1883.16  1132.8  1885.3
#Mann= 3 , 0 , 0
       0      .1       0   529.8    .045       0   544.8      .1       0
Bank Sta=529.8,544.8
XS Rating Curve= 0 ,0
Exp/Cntr=0.3,0.1

Type RM Length L Ch R = 1 ,43616   ,271.1,272.6,274.1
XS GIS Cut Line= 3
     1877056.068      301492.942     1877075.783      301879.093
      1877163.81      302412.268
#Sta/Elev= 30
       0 1923.64    39.7 1911.29    59.5 1901.13    69.4 1897.36    79.3 1895.42
   148.7  1858.7   158.6 1854.71   168.5 1853.45   218.1 1828.57     228 1824.17
   247.8 1817.48   257.8 1816.93   317.2 1794.74   327.2 1792.03   337.1 1791.11
   495.5 1787.62   506.7 1787.48   510.5 1787.68   536.8 1790.94   546.8  1791.3
   576.8 1794.71   596.8 1795.87   626.8 1801.52   646.8 1803.75   666.9 1807.32
   686.9 1809.88   746.9 1814.11     817 1822.92     877 1826.26     927 1835.11
#Mann= 3 , 0 , 0
       0      .1       0   495.5    .045       0   510.5      .1       0
Bank Sta=495.5,510.5
XS Rating Curve= 0 ,0
Exp/Cntr=0.3,0.1

Type RM Length L Ch R = 1 ,43342.9 ,326.9,320.2,313.2
XS GIS Cut Line= 3
     1876863.558      301440.547      1876809.29      301822.794
     1876879.747      302541.336
#Sta/Elev= 30
       0  1955.3    19.8 1944.11    29.7 1943.04   108.9 1895.23   118.8 1894.72
   168.3 1872.77     198 1857.59   207.9    1856   217.8 1851.85   267.3 1826.99
     297 1814.63   316.8 1811.57   376.2 1794.17     396 1790.57   550.3 1786.74
   554.2 1786.68   565.3 1786.91   643.2 1794.87   653.1  1796.8   672.9 1803.07
   682.8 1803.47   692.7 1806.38   771.8 1832.46   791.6 1835.52   821.2 1844.55
     841 1848.51     930 1856.72    1029 1862.23  1068.5 1859.39  1108.1 1851.97
#Mann= 3 , 0 , 0
       0      .1       0   550.3    .045       0   565.3      .1       0
Bank Sta=550.3,565.3
XS Rating Curve= 0 ,0
Exp/Cntr=0.3,0.1

Type RM Length L Ch R = 1 ,43021.5 ,290.2,298.8,294.2
XS GIS Cut Line= 3
     1876309.572      301526.656     1876622.666      302020.292
     1876761.808      302557.579
#Sta/Elev= 30
       0 1939.74     9.9  1940.5    29.7 1938.75    49.5 1933.13    79.3 1918.85
   118.9 1895.99   138.7  1890.5   237.8 1840.06   257.6 1835.47   287.3 1822.06
   307.1 1815.91   346.8 1806.09   356.7 1805.95   396.3 1794.34   406.2 1792.64
   574.6  1786.5   577.1 1786.53   592.1 1786.83   713.4 1790.33   782.8  1795.7
   832.3 1802.19     872 1809.98   881.9 1809.06   921.5 1815.07   971.1 1820.04
  1000.8  1819.9  1070.2 1814.63  1099.9 1813.82  1119.8 1815.33  1139.6 1820.32
#Mann= 3 , 0 , 0
       0      .1       0   577.1    .045       0   592.1      .1       0
Bank Sta=577.1,592.1
XS Rating Curve= 0 ,0
Exp/Cntr=0.3,0.1

Type RM Length L Ch R = 1 ,42721.5 ,304.9,300.9,301.9
XS GIS Cut Line= 3
     1876225.565      301555.787     1876352.415      302103.862
     1876580.298      302609.985
#Sta/Elev= 30
       0 1905.38    19.7 1904.42    39.5 1901.48    69.1 1892.36    88.8 1888.44
   167.8 1858.26   177.6 1858.14   266.5 1817.15   286.2 1812.28   325.7 1795.54
   345.4 1789.44   555.1 1784.59   570.1 1784.57   572.5 1784.56   592.3 1786.66
   612.1 1793.83   641.9 1798.36   661.7 1806.29   681.5 1810.39   760.8 1844.08
   790.5 1850.33   810.4 1853.81   869.8 1859.91   889.6 1859.92     969 1869.48
   988.8 1869.59  1028.4 1873.94    1078 1882.14  1097.8 1882.74  1117.6 1886.56
#Mann= 3 , 0 , 0
       0      .1       0   555.1    .045       0   570.1      .1       0
Bank Sta=555.1,570.1
XS Rating Curve= 0 ,0
Exp/Cntr=0.3,0.1

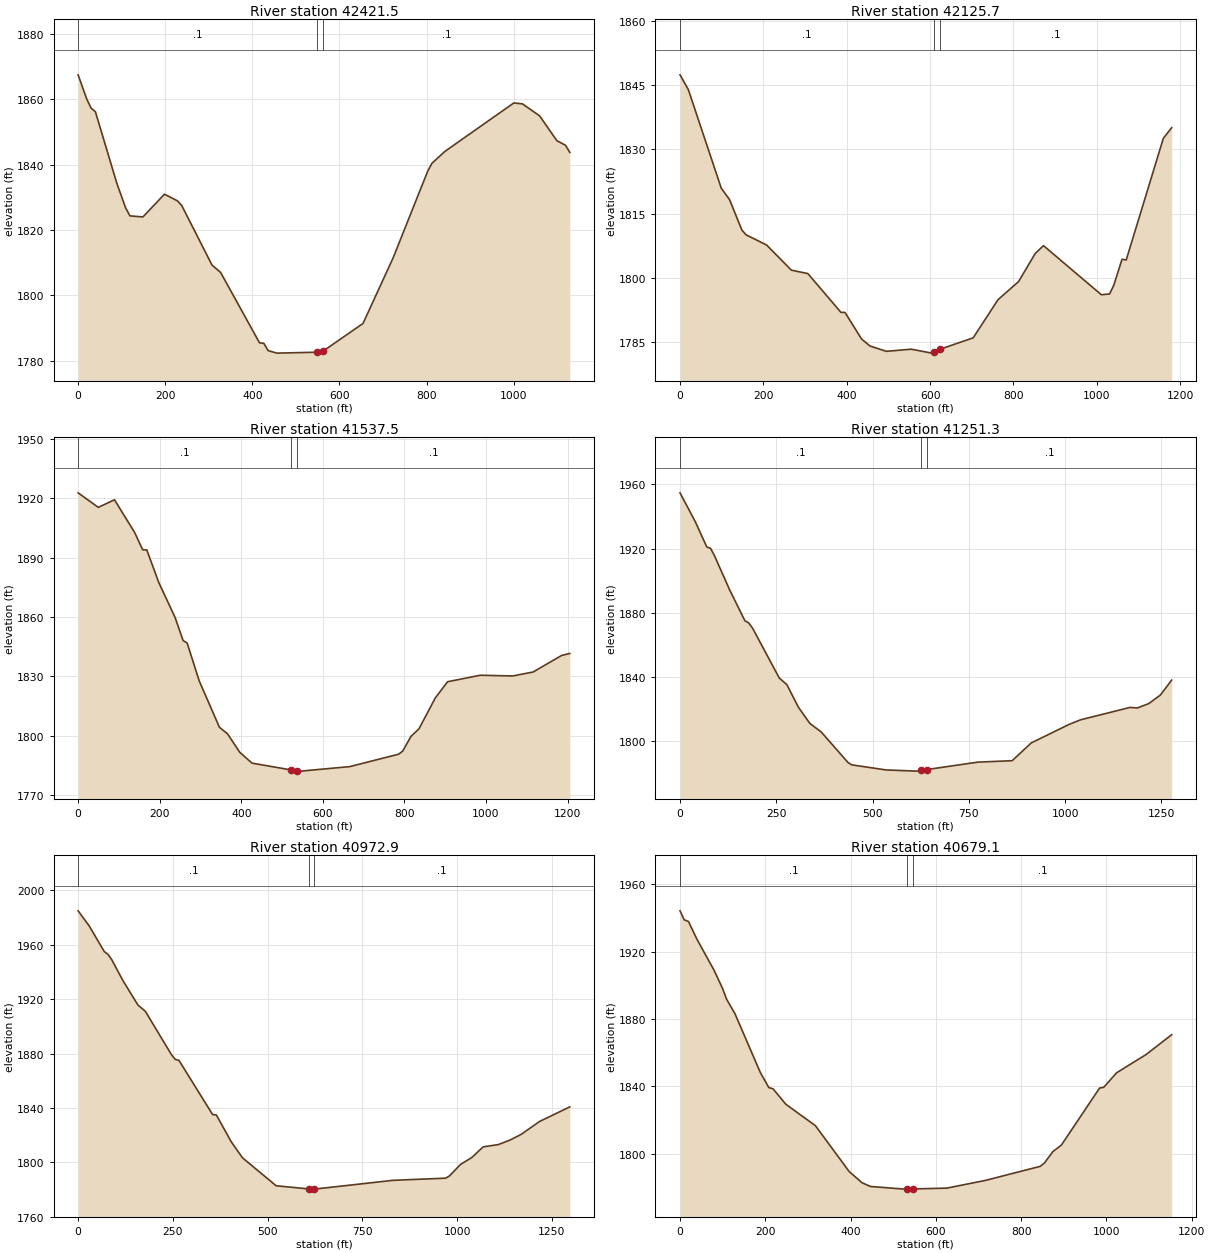
Type RM Length L Ch R = 1 ,42421.5 ,301.5,295.8,298.3
XS GIS Cut Line= 3
     1875972.984       301592.63     1876095.434      302134.291
     1876255.153      302685.241
#Sta/Elev= 30
       0 1867.48    19.8 1860.07    29.8  1857.3    39.7 1856.19    89.2 1834.17
   109.1  1826.8     119 1824.34   148.8 1824.01   198.3 1830.97   228.1 1828.94
     238 1827.48   307.4 1809.31   327.2 1807.04   416.5 1785.52   426.4 1785.36
   436.3 1783.14   456.2 1782.36   547.8 1782.64   562.8    1783   654.2 1791.43
   723.5 1811.54   802.6 1837.96   812.5 1840.43   842.2 1844.05  1000.4 1858.87
  1020.2  1858.6  1059.7 1854.94  1099.3 1847.34  1119.1 1845.94    1129 1843.76
#Mann= 3 , 0 , 0
       0      .1       0   547.8    .045       0   562.8      .1       0
Bank Sta=547.8,562.8
XS Rating Curve= 0 ,0
Exp/Cntr=0.3,0.1

Type RM Length L Ch R = 1 ,42125.7 ,574.6,588,595.3
XS GIS Cut Line= 3
     1875836.838      301602.893     1875824.622      302008.488
     1875979.607       302766.61
#Sta/Elev= 30
       0 1847.39    19.8 1843.98      99 1820.91   118.8 1818.27   148.5 1811.13
   158.4 1810.04   207.8 1807.65   267.2 1801.78   306.8 1800.98     386 1791.94
   395.9  1791.9   435.5 1785.72   455.4 1784.09   495.1 1782.83   554.6 1783.33
   604.2 1782.41   609.8 1782.62   624.8 1783.35   703.4 1785.98   762.9 1794.88
   812.5 1799.14   852.2 1805.67     872 1807.51  1010.9 1796.04  1030.8 1796.23
  1040.7 1798.26  1060.5 1804.33  1070.5 1804.15  1159.7 1832.59  1179.6 1835.05
#Mann= 3 , 0 , 0
       0      .1       0   609.8    .045       0   624.8      .1       0
Bank Sta=609.8,624.8
XS Rating Curve= 0 ,0
Exp/Cntr=0.3,0.1

Type RM Length L Ch R = 1 ,41537.5 ,254.3,285.2,281.7
XS GIS Cut Line= 3
      1875604.72      301541.809     1875565.627      301896.094
     1875519.203      302743.936
#Sta/Elev= 30
       0 1922.87    49.5 1915.51    89.1 1919.35   138.6 1902.81   158.4 1894.03
   168.3    1894     198 1877.37   237.6 1859.87   257.4 1848.11   267.3 1846.88
     297 1827.65   346.5  1804.2   366.4 1800.87   396.4 1791.52   426.4 1786.06
   521.9 1782.63   536.9 1782.08   546.2 1782.01   666.1  1784.3     786 1790.58
     796 1792.16     816 1799.55   835.9 1803.46   875.9 1819.07   905.9 1827.25
   985.8 1830.53  1065.7 1830.18  1115.6 1832.17  1185.6 1840.56  1205.6 1841.57
#Mann= 3 , 0 , 0
       0      .1       0   521.9    .045       0   536.9      .1       0
Bank Sta=521.9,536.9
XS Rating Curve= 0 ,0
Exp/Cntr=0.3,0.1

Type RM Length L Ch R = 1 ,41251.3 ,271.2,277.3,273.8
XS GIS Cut Line= 3
     1875379.782      301527.703     1875416.583      302409.197
      1875443.46      302802.576
#Sta/Elev= 30
       0 1954.78    39.6 1936.81    69.4  1921.1    79.3 1920.14    89.2 1915.73
   128.9 1894.26   168.5 1875.02   178.4  1873.7   188.4 1870.41   257.7 1839.34
   277.6 1835.15   307.3 1821.15     337 1811.08   366.8 1805.66   436.2 1786.64
   446.1 1785.18   535.3 1782.01   614.6 1781.28   626.3  1781.7   641.3 1782.27
   773.2 1786.88   862.4 1787.78   911.8 1798.84  1010.4 1810.42    1040 1813.27
  1168.1 1820.98  1187.8 1820.68  1217.4 1823.42    1247 1828.66  1276.6    1838
#Mann= 3 , 0 , 0
       0      .1       0   626.3    .045       0   641.3      .1       0
Bank Sta=626.3,641.3
XS Rating Curve= 0 ,0
Exp/Cntr=0.3,0.1

Type RM Length L Ch R = 1 ,40972.9 ,210.3,292.7,304.8
XS GIS Cut Line= 3
     1875291.972      301436.745     1875228.445      301925.415
     1875010.987      302699.955
#Sta/Elev= 30
       0    1985    29.6 1973.72      69 1955.02    78.8    1953    88.7 1949.05
   118.3 1933.65   157.7 1915.75   177.4 1911.09   246.4 1879.14   256.2 1875.71
   266.1 1874.98   354.8 1835.14   364.7 1834.83   404.1 1815.08   433.6 1803.33
   522.6 1782.73   608.3 1780.43     612 1780.27   623.3 1780.28   830.5 1786.73
   969.5 1788.33   979.4 1789.88  1009.2 1798.48    1039 1803.57  1068.8 1811.37
  1108.6 1813.04  1138.4 1816.21  1168.2  1820.4  1217.8 1830.08  1297.3 1840.77
#Mann= 3 , 0 , 0
       0      .1       0   608.3    .045       0   623.3      .1       0
Bank Sta=608.3,623.3
XS Rating Curve= 0 ,0
Exp/Cntr=0.3,0.1

Type RM Length L Ch R = 1 ,40679.1 ,403.4,406,394.6
XS GIS Cut Line= 3
      1875196.37      301489.915     1875072.071      301866.774
     1874906.532      302604.605
#Sta/Elev= 30
       0 1944.14     9.9  1938.8    19.8 1937.83    39.7  1927.3    79.4 1909.14
    99.2 1898.45   109.1 1891.83     129 1883.07   188.5 1848.22   208.3 1839.35
   218.3  1838.6     248 1829.51   317.5 1816.78   396.8 1789.55   426.7 1782.95
   446.6 1780.73   526.2 1779.15   532.2 1779.16   547.2 1779.27   625.7 1779.74
   715.2 1784.26   844.6 1792.64   854.5  1794.6   874.4 1801.41   894.3 1805.24
   983.9 1839.05   993.8 1839.54  1023.7 1848.09  1093.3    1859    1153 1870.71
#Mann= 3 , 0 , 0
       0      .1       0   532.2    .045       0   547.2      .1       0
Bank Sta=532.2,547.2
XS Rating Curve= 0 ,0
Exp/Cntr=0.3,0.1

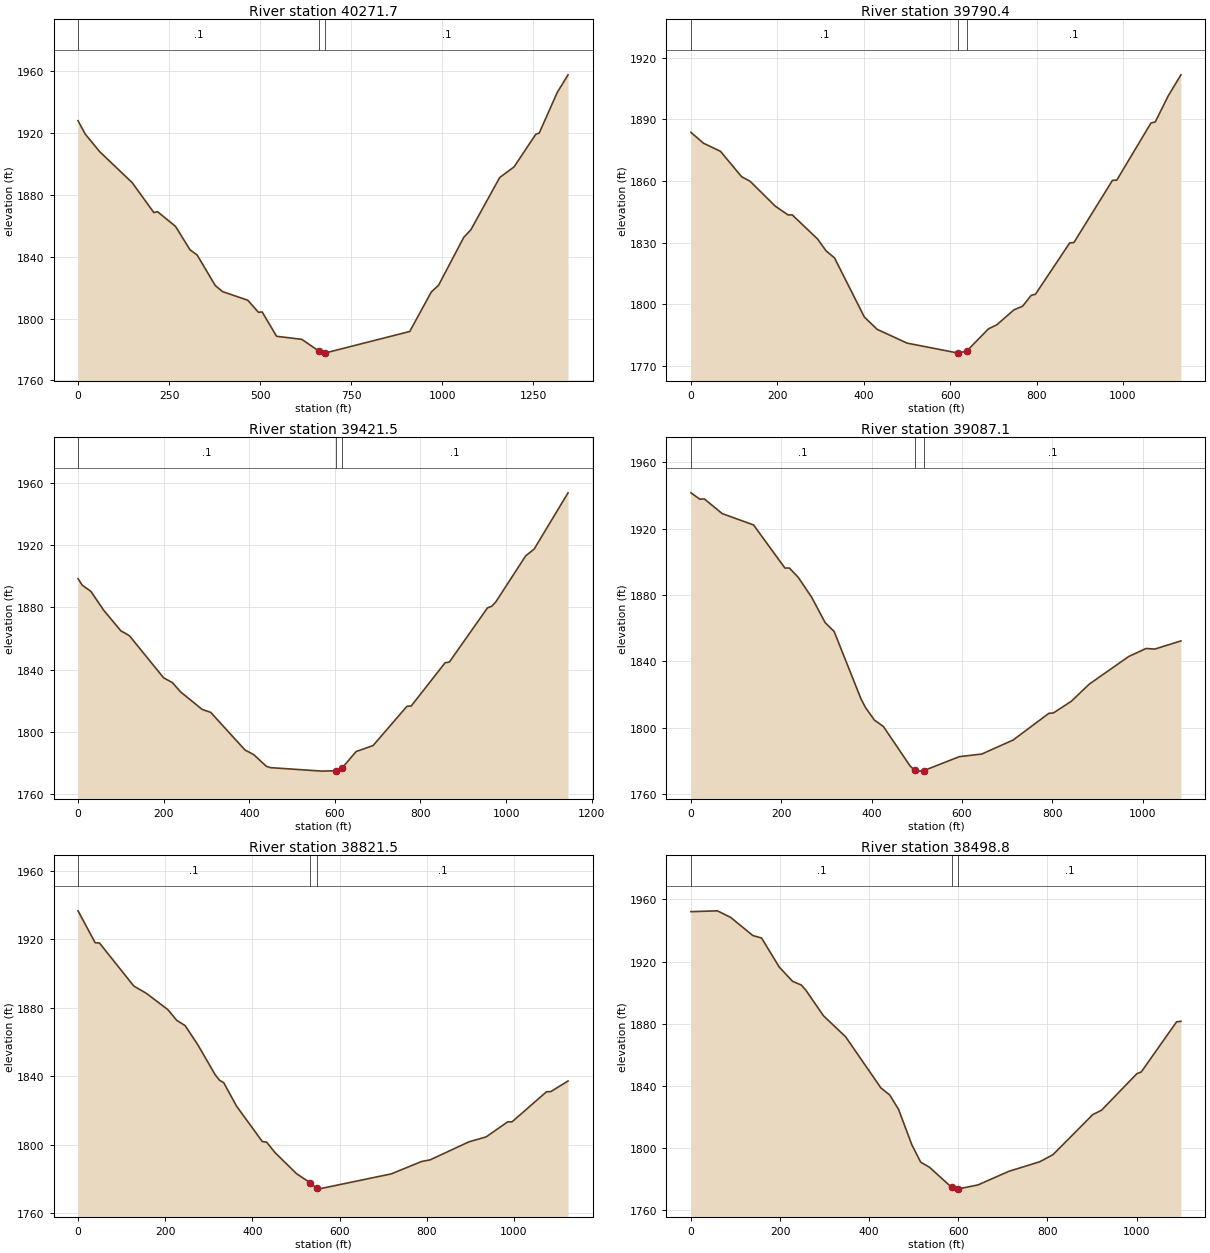
Type RM Length L Ch R = 1 ,40271.7 ,428.2,480.5,475
XS GIS Cut Line= 3
     1874896.265      301283.504     1874786.804      301817.924
     1874666.475      302609.551
#Sta/Elev= 30
       0 1928.07    19.8 1919.41    59.5 1908.03   148.8 1887.97   208.3 1868.59
   218.2 1869.21   267.8 1859.67   307.5 1844.56   327.3 1841.11   376.9 1821.42
   396.7 1817.46   466.2 1811.86   495.9    1804   505.8 1804.28   545.5  1788.5
   614.7 1786.52     663 1778.74     674  1777.6     678 1777.64   911.3 1791.62
   970.6 1817.22   990.4 1821.51  1059.6 1852.51  1079.3 1857.49  1158.4 1891.28
    1198  1898.2  1257.3  1919.2  1267.2 1920.15  1316.6 1946.42  1346.2 1957.78
#Mann= 3 , 0 , 0
       0      .1       0     663    .045       0     678      .1       0
Bank Sta=663,678
XS Rating Curve= 0 ,0
Exp/Cntr=0.3,0.1

Type RM Length L Ch R = 1 ,39790.4 ,363.2,367.7,370.8
XS GIS Cut Line= 3
     1874458.791      301353.671     1874468.564      301715.287
     1874461.106      302487.717
#Sta/Elev= 30
       0  1883.7    29.3 1878.37    68.4 1874.46   117.3 1862.07   136.9 1859.87
   195.5 1847.68   224.9 1843.45   234.6 1843.46   293.3 1831.68   312.9 1825.93
   332.4  1822.5   401.4  1793.7   431.1 1787.67   500.4 1780.96   619.2 1776.08
     639  1777.2   688.6 1787.89   708.4 1789.95     748 1797.22   767.8 1798.96
   787.6 1804.22   797.5 1804.78   876.7 1829.77   886.6 1830.01   975.8 1860.31
   985.7 1860.38  1064.9 1888.26  1074.8 1888.75  1104.5 1901.33  1134.2 1911.73
#Mann= 3 , 0 , 0
       0      .1       0   619.2    .045       0     639      .1       0
Bank Sta=619.2,639
XS Rating Curve= 0 ,0
Exp/Cntr=0.3,0.1

Type RM Length L Ch R = 1 ,39421.5 ,328.9,333,336.9
XS GIS Cut Line= 3
     1874250.746      301365.397     1874187.402      301972.197
     1874134.994      302504.306
#Sta/Elev= 30
       0 1898.31      10 1894.13      30 1890.18      60 1878.06     100 1864.87
     120 1861.75     200  1834.7     220 1831.74     240 1825.59     290 1814.45
     310 1812.56   390.1 1788.41   410.1 1785.52   440.1 1777.93   450.1 1777.08
   570.1 1774.86   602.6  1775.1   617.6 1777.07   649.7 1787.42   689.3 1791.26
   768.5 1816.47   778.4 1816.65   857.6 1844.38   867.5 1844.83   956.6  1879.6
   966.6 1880.64   976.4 1883.56  1045.8 1912.94  1065.6  1917.3  1144.8 1953.39
#Mann= 3 , 0 , 0
       0      .1       0   602.6    .045       0   617.6      .1       0
Bank Sta=602.6,617.6
XS Rating Curve= 0 ,0
Exp/Cntr=0.3,0.1

Type RM Length L Ch R = 1 ,39087.1 ,270.5,265.3,260.3
XS GIS Cut Line= 3
     1874069.383      301357.642     1873816.496      302222.587
     1873706.977      302369.403
#Sta/Elev= 30
       0  1941.6    19.8 1937.75    29.7 1937.93    69.3 1929.06   138.6 1922.23
     208 1896.23   217.9 1896.23   237.7 1890.56   267.4 1878.51   297.1 1863.28
   316.9 1857.97   376.3 1817.34   386.2 1812.13     406 1804.51   425.8 1800.68
   485.2 1776.77     495 1774.28     505 1773.71     515 1773.99   594.2 1782.46
   643.7 1784.02     713 1792.47   792.2 1808.59   802.1 1808.79   841.7 1815.84
   881.4 1826.16   968.6 1842.84  1007.2 1847.69  1026.5 1847.34  1084.3 1852.27
#Mann= 3 , 0 , 0
       0      .1       0     495    .045       0     515      .1       0
Bank Sta=495,515
XS Rating Curve= 0 ,0
Exp/Cntr=0.3,0.1

Type RM Length L Ch R = 1 ,38821.5 ,319.7,321.8,322.9
XS GIS Cut Line= 3
     1873734.378      301228.879     1873683.974      301767.131
     1873625.555      302347.626
#Sta/Elev= 30
       0 1936.66    39.3 1918.03    49.2 1917.84   127.8 1892.73   157.3 1888.34
   206.4 1878.82   226.1 1872.72   245.7 1869.55   275.2 1858.19   314.5 1840.89
   324.4 1837.67   334.2  1836.2   363.7 1822.45   422.7  1801.8   432.5 1801.45
   452.1 1795.28   501.3 1782.99   533.1 1777.59   548.1 1774.35   550.5 1773.98
   718.6 1782.89   787.8 1790.11   807.6 1791.08   896.6 1801.62   936.2 1804.52
   985.6 1813.31   995.5 1813.31  1074.6 1830.89  1084.5 1831.01    1124 1837.18
#Mann= 3 , 0 , 0
       0      .1       0   533.1    .045       0   548.1      .1       0
Bank Sta=533.1,548.1
XS Rating Curve= 0 ,0
Exp/Cntr=0.3,0.1

Type RM Length L Ch R = 1 ,38498.8 ,392.9,397.3,401.8
XS GIS Cut Line= 3
     1873514.949      301218.846     1873408.029      301763.594
     1873314.757      302299.847
#Sta/Elev= 30
       0 1952.11    59.5 1952.65    89.2 1948.42   138.8 1936.78   158.6 1935.13
   198.3 1916.43     228 1907.32   247.8 1904.87   257.7 1901.65   297.4 1885.13
     347 1871.63   426.3 1838.69   446.1 1834.15   465.9 1824.87   495.7 1802.11
   515.5 1790.94   535.3 1787.64     585  1774.7   594.7 1773.56     600 1773.68
   644.2 1776.29   713.5 1785.03   782.8 1791.19   812.4 1795.74   901.5  1821.5
   921.3 1824.33  1000.5 1847.84  1010.4 1848.96  1089.6 1881.18  1099.4 1881.59
#Mann= 3 , 0 , 0
       0      .1       0     585    .045       0     600      .1       0
Bank Sta=585,600
XS Rating Curve= 0 ,0
Exp/Cntr=0.3,0.1