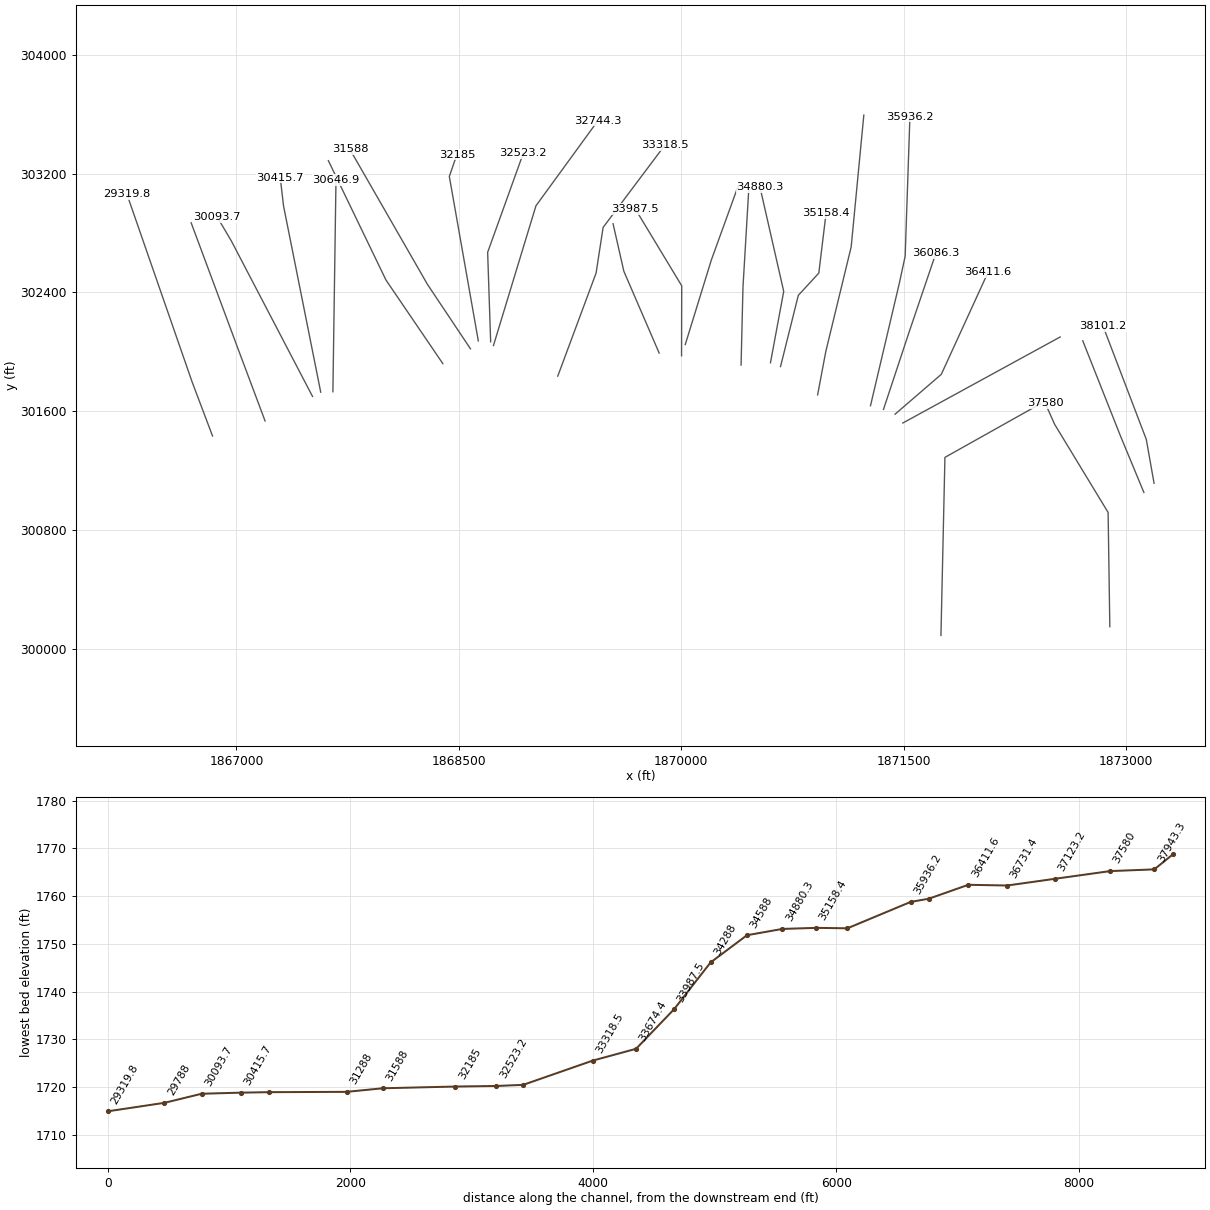
HEC-RAS study SndlckCrk.prj: SndlckCrk

--- SndlckCrk.g01 (geometry) --- (continued)

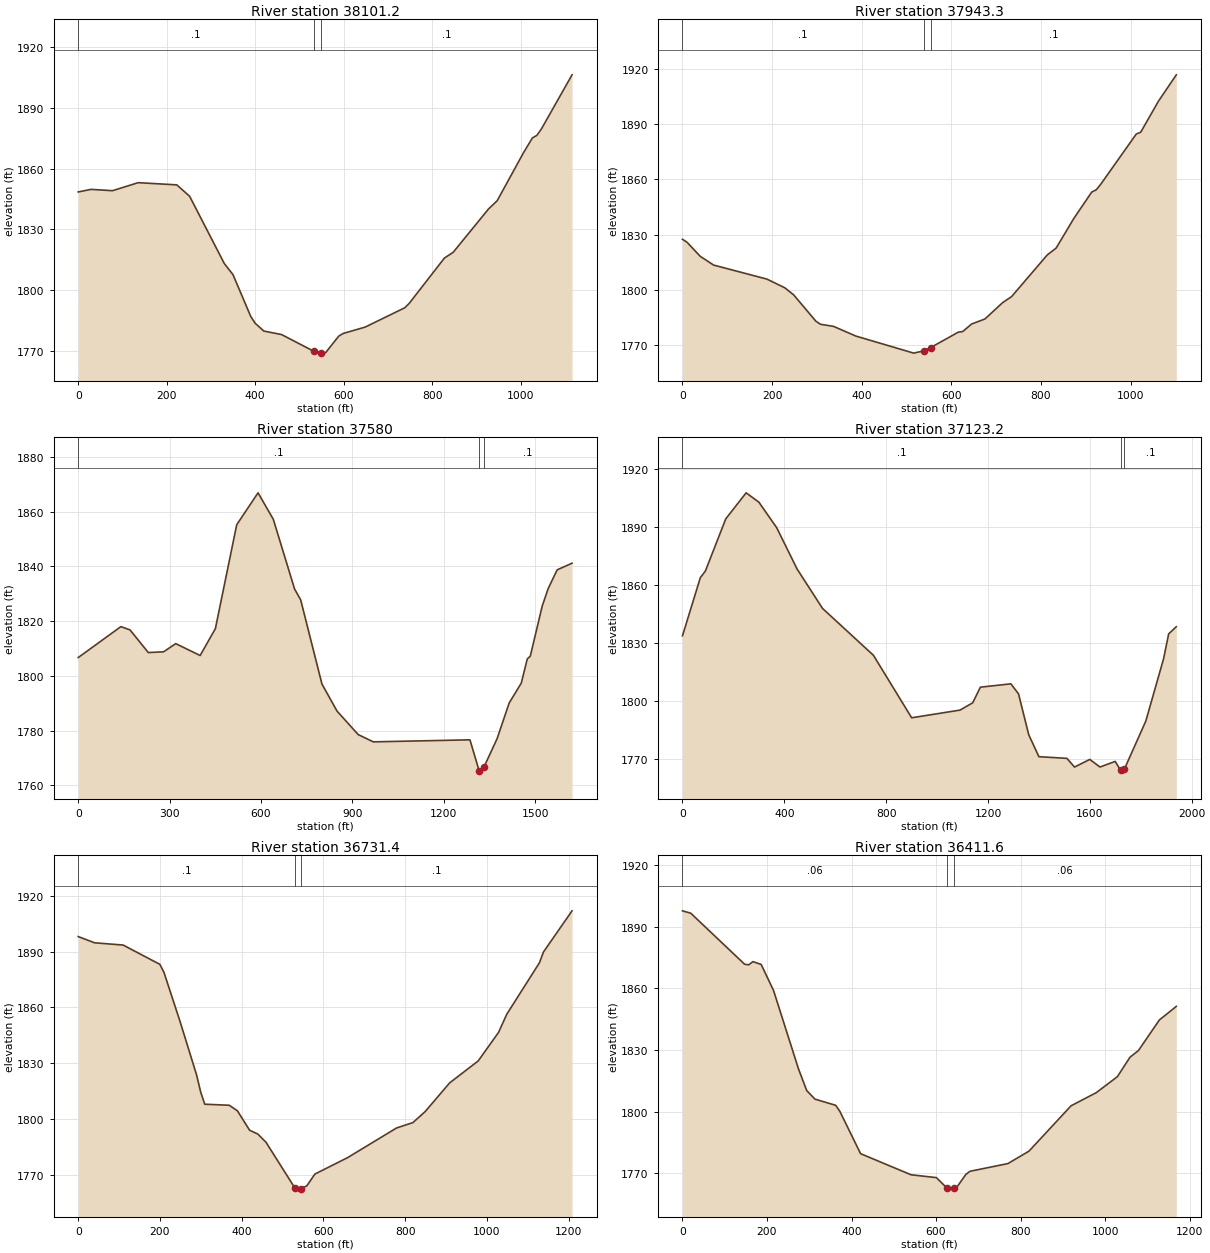
Type RM Length L Ch R = 1 ,38101.2 ,157.6,157.9,158.2
XS GIS Cut Line= 3
      1873187.21      301113.272     1873134.803      301408.952
     1872843.434      302171.276
#Sta/Elev= 30
       0  1848.5    29.1 1849.78    77.5 1849.12   135.6 1853.09   222.8    1852
   251.9 1846.35   330.2 1813.12     350 1807.57   389.9 1787.02   399.8 1783.64
   419.7 1779.72   459.5 1778.02   532.9 1769.71   547.9 1768.85   549.1 1768.82
   559.1 1768.99   588.9 1777.21   598.9 1778.54   648.6 1781.68   738.2 1791.24
   748.2  1793.4   827.8  1815.8   847.7 1818.67   927.3 1840.01   947.2 1844.18
  1006.9 1867.98  1026.8 1875.21  1036.8 1876.46  1046.7 1879.48  1116.4  1906.4
#Mann= 3 , 0 , 0
       0      .1       0   532.9    .045       0   547.9      .1       0
Bank Sta=532.9,547.9
XS Rating Curve= 0 ,0
Exp/Cntr=0.3,0.1

Type RM Length L Ch R = 1 ,37943.3 ,359.5,363.3,367.1
XS GIS Cut Line= 3
     1873118.505      301051.533     1872958.882       301436.44
     1872706.462      302073.347
#Sta/Elev= 30
       0 1827.44     9.9  1825.9    39.7 1818.19    69.4 1813.45   188.5 1805.81
   228.2  1801.1     248 1797.27   297.6 1782.94   307.6 1781.29   337.3  1780.1
   386.9 1774.85     516 1765.58   538.8 1766.84   553.8 1768.62   615.3 1776.96
   625.2 1777.31   645.1  1781.4   674.8 1784.13   714.6 1793.09   734.4 1796.32
   813.8 1818.93   833.7 1822.68   873.4 1838.87   913.1 1853.12   923.1 1854.35
     933 1857.29  1012.4 1884.65  1022.4 1885.67  1062.1 1902.56  1101.8 1916.85
#Mann= 3 , 0 , 0
       0      .1       0   538.8    .045       0   553.8      .1       0
Bank Sta=538.8,553.8
XS Rating Curve= 0 ,0
Exp/Cntr=0.3,0.1

Type RM Length L Ch R = 1 ,37580   ,493.5,456.8,420.2
XS GIS Cut Line= 4
     1872888.941      300146.658     1872877.362        300916.7
     1872517.247       301509.74     1872453.109      301652.676
#Sta/Elev= 30
       0  1806.7     140    1818     170  1816.8     230 1808.53     280 1808.79
     320 1811.79   400.1 1807.45   450.1 1817.26   520.1 1855.19   590.1 1866.87
   640.1 1857.23   710.1 1831.72   730.1 1827.76   799.9 1797.01   849.4 1787.14
   918.8 1778.57   968.4 1775.91  1285.5 1776.65    1316 1765.25  1325.2 1765.22
    1331 1766.58  1374.7  1777.1  1414.4 1790.13    1454 1797.36  1473.7 1806.22
  1483.5 1807.19  1522.7 1825.51  1542.3 1831.89  1571.6 1838.72  1620.6 1841.17
#Mann= 3 , 0 , 0
       0      .1       0    1316    .045       0    1331      .1       0
Bank Sta=1316,1331
XS Rating Curve= 0 ,0
Exp/Cntr=0.3,0.1

Type RM Length L Ch R = 1 ,37123.2 ,392.8,391.7,390.6
XS GIS Cut Line= 3
     1871750.342      300088.018     1871777.218      301287.701
     1872422.262      301649.316
#Sta/Elev= 30
       0 1833.64      70  1863.7      90 1867.17     170 1894.17     250 1907.63
     300  1902.8     370  1889.6     450 1868.23     550 1847.81     750 1823.54
     900 1791.21    1090 1795.18    1140 1798.98    1170 1807.05  1289.9 1808.78
  1319.9 1803.55  1359.9 1782.46  1399.8 1771.08  1509.8 1770.21  1539.8  1765.7
  1599.7 1769.67  1639.7 1765.72  1699.6 1768.63  1720.9 1764.01  1729.6  1763.6
  1735.9 1764.74  1819.6 1789.46  1889.5 1821.72  1909.5 1834.62  1939.5 1838.35
#Mann= 3 , 0 , 0
       0      .1       0  1720.9    .045       0  1735.9      .1       0
Bank Sta=1720.9,1735.9
XS Rating Curve= 0 ,0
Exp/Cntr=0.3,0.1

Type RM Length L Ch R = 1 ,36731.4 ,305.3,319.7,334.2
XS GIS Cut Line= 2
     1871493.593      301519.355     1872554.202      302098.892
#Sta/Elev= 30
       0 1898.15      40  1894.8   109.9 1893.59   199.8  1883.2   209.8  1878.9
   249.7  1852.1   289.7 1823.65   299.7 1814.48   309.6 1807.91   369.6 1807.35
   389.6 1804.36   419.5 1793.89   439.5 1791.86   459.5 1787.45   529.9 1762.93
   539.4  1762.2   544.9 1762.44   559.4 1763.94   579.3 1770.32   659.2 1779.14
   779.1 1795.12   819.1 1798.02     849 1803.91     909 1819.38   978.9  1831.2
  1028.8  1846.6  1048.8 1856.32  1128.7 1884.02  1138.7 1889.87  1208.6 1912.01
#Mann= 3 , 0 , 0
       0      .1       0   529.9    .045       0   544.9      .1       0
Bank Sta=529.9,544.9
XS Rating Curve= 0 ,0
Exp/Cntr=0.3,0.1

Type RM Length L Ch R = 1 ,36411.6 ,323,325.2,327.4
XS GIS Cut Line= 3
     1871440.986      301578.627     1871752.785      301847.227
     1872068.285      302535.501
#Sta/Elev= 30
       0 1897.66    19.6  1896.5     147  1871.7   156.8  1871.4   166.6 1872.97
   186.2  1871.6   215.6 1858.88   274.4  1820.9     294 1810.27   313.6  1806.1
   362.6  1803.1   372.4 1800.18   421.5 1779.59     541 1769.32   600.8 1767.95
   626.8  1762.7   630.7 1762.35   641.8 1762.99   650.6 1763.67   670.6  1769.5
   680.5 1771.03   770.2 1774.77     820 1780.81   919.6 1802.86   979.4 1809.27
  1029.2 1817.02  1059.1 1826.48    1079 1829.71  1128.8 1844.63  1168.7  1851.2
#Mann= 3 , 0 , 0
       0     .06       0   626.8    .045       0   641.8     .06       0
Bank Sta=626.8,641.8
XS Rating Curve= 0 ,0
Exp/Cntr=0.3,0.1

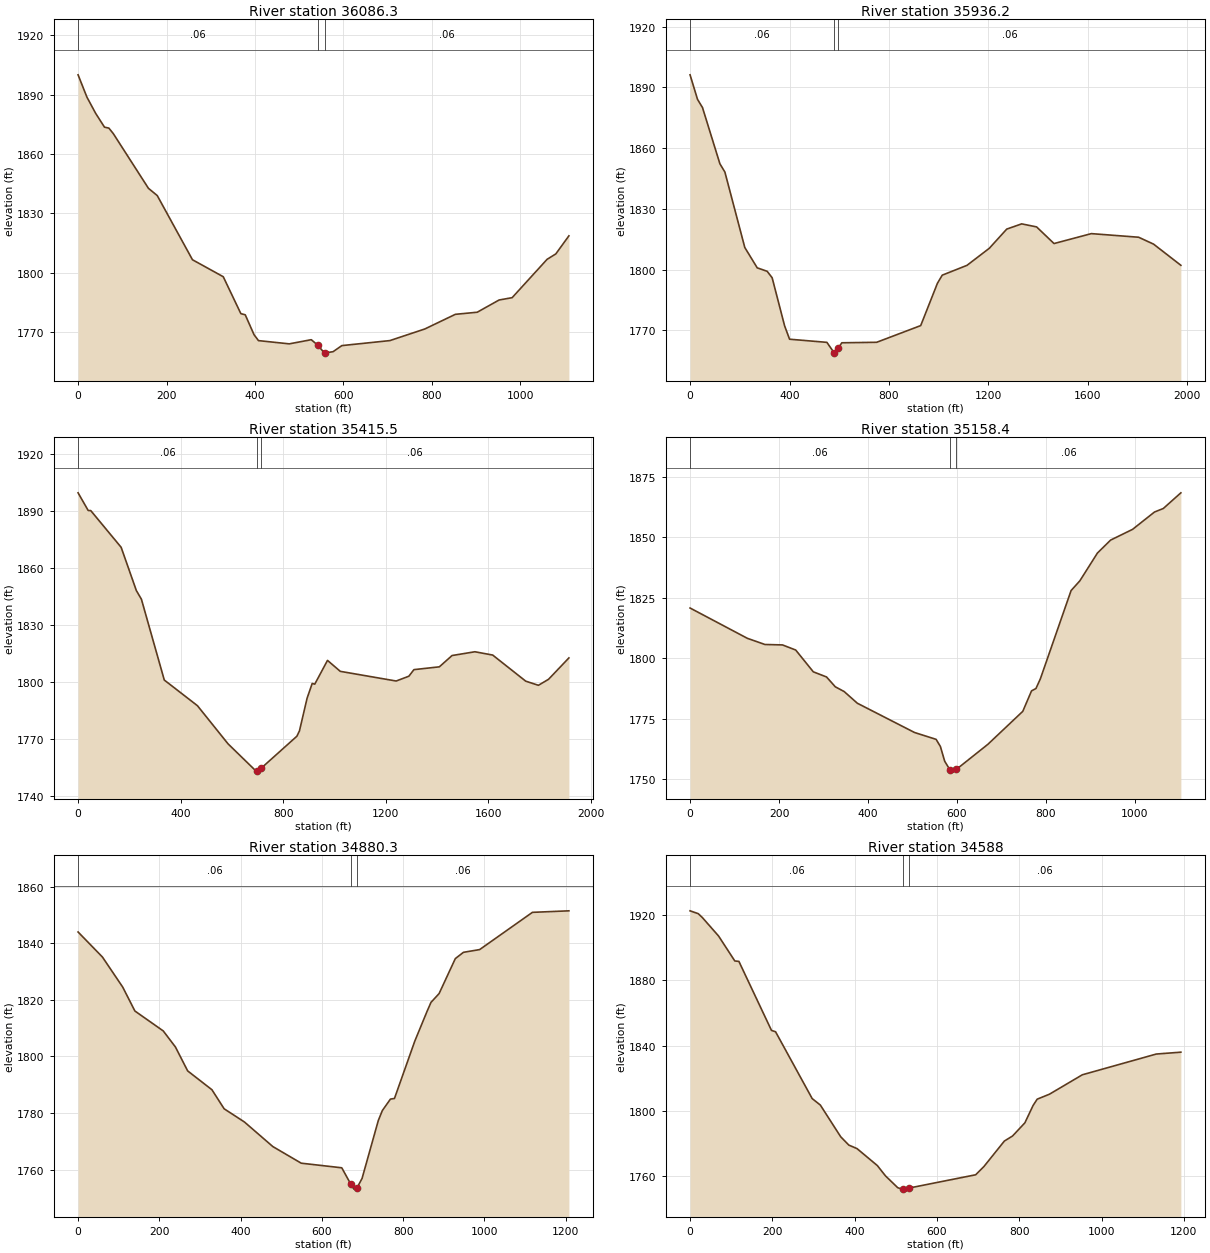
Type RM Length L Ch R = 1 ,36086.3 ,147.3,150.2,152.7
XS GIS Cut Line= 3
     1871363.012      301611.145     1871535.135      302130.341
     1871716.281      302663.018
#Sta/Elev= 30
       0 1899.98    19.9 1888.77    39.8  1880.5    59.7 1873.56    69.6 1873.07
    79.6  1870.3   159.1 1842.66     179    1839   258.6  1806.6   328.2 1798.02
     368 1779.38   377.9  1778.8   397.8 1768.75   407.8 1765.76   477.4 1764.12
   527.1 1766.22   542.6 1763.34   556.8 1759.44   557.6 1759.49   576.6 1760.18
   596.3 1763.24   704.9 1765.77   783.9 1771.64     853 1779.04   902.3 1780.09
   951.7 1786.26   981.3 1787.45  1060.3 1806.81    1080 1809.54  1109.6 1818.67
#Mann= 3 , 0 , 0
       0     .06       0   542.6    .045       0   557.6     .06       0
Bank Sta=542.6,557.6
XS Rating Curve= 0 ,0
Exp/Cntr=0.3,0.1

Type RM Length L Ch R = 1 ,35936.2 ,521.3,520.5,518.6
XS GIS Cut Line= 4
     1871275.378      301635.855     1871470.426      302463.791
     1871509.053      302642.734     1871541.145      303582.646
#Sta/Elev= 30
       0 1896.21      30 1884.11      50 1880.05   120.1 1852.26   140.1  1848.2
   220.2 1810.93   270.2 1800.88   310.2 1799.17   330.2 1795.98   380.3 1772.24
   400.3 1765.63   550.4 1764.08   580.4 1758.76   580.8 1758.79   595.8 1761.13
   610.4 1763.87   750.5 1764.11   927.7 1772.36   995.1  1793.3  1014.4 1797.27
  1113.7  1802.1  1203.8 1810.56  1273.8 1820.02  1333.8  1822.6  1393.8  1821.1
  1463.9 1812.88    1614 1817.78    1804    1816  1864.1 1812.61  1974.1 1802.14
#Mann= 3 , 0 , 0
       0     .06       0   580.8    .045       0   595.8     .06       0
Bank Sta=580.8,595.8
XS Rating Curve= 0 ,0
Exp/Cntr=0.3,0.1

Type RM Length L Ch R = 1 ,35415.5 ,268.5,257,245.5
XS GIS Cut Line= 4
      1870918.84      301708.797     1870973.815      302000.166
     1871145.146      302705.923     1871230.394      303593.745
#Sta/Elev= 30
       0 1899.75    39.5 1890.44    49.4  1890.4     168 1871.07   227.3  1848.3
   247.1 1843.72   336.3 1801.19   465.6 1787.69     585 1767.61   694.5 1753.24
   699.6 1753.35   714.6 1754.81   853.6 1771.62   863.6 1774.43   893.4 1791.63
   913.3 1799.39   923.3 1799.03     973 1811.54  1022.8 1805.77  1240.8 1800.68
  1290.3  1803.2  1310.2 1806.67  1409.3 1808.14  1458.8 1814.09    1548 1816.08
  1617.4 1814.34  1746.2 1800.61  1795.8 1798.42  1835.4  1801.6  1914.7 1812.84
#Mann= 3 , 0 , 0
       0     .06       0   699.6    .045       0   714.6     .06       0
Bank Sta=699.6,714.6
XS Rating Curve= 0 ,0
Exp/Cntr=0.3,0.1

Type RM Length L Ch R = 1 ,35158.4 ,256.9,278.1,299.3
XS GIS Cut Line= 4
     1870668.779      301899.376     1870788.732      302379.495
     1870926.846      302529.281     1870975.648      302931.081
#Sta/Elev= 30
       0  1820.8   128.7 1808.27   168.3 1805.71   207.8 1805.53   237.5 1803.42
   277.1  1794.4   306.8 1792.28   326.6  1788.2   346.4 1786.25   376.1 1781.41
   504.6 1769.31   553.1 1766.48   562.8 1763.52   572.5  1757.4   583.9 1753.98
   591.9 1753.33   598.9 1754.08   669.5 1764.42     748 1778.06   767.7 1786.53
   777.6 1787.49   787.5  1791.5   856.6 1828.02   876.3 1832.04   915.8 1843.53
   945.4 1848.88   994.8 1853.33  1044.1  1860.5  1063.9 1861.96  1103.4 1868.44
#Mann= 3 , 0 , 0
       0     .06       0   583.9    .045       0   598.9     .06       0
Bank Sta=583.9,598.9
XS Rating Curve= 0 ,0
Exp/Cntr=0.3,0.1

Type RM Length L Ch R = 1 ,34880.3 ,297.2,292.2,286.5
XS GIS Cut Line= 3
     1870600.996      301925.269     1870690.279      302406.231
       1870530.6      303106.878
#Sta/Elev= 30
       0 1844.01    59.9 1835.16   109.8 1824.54   139.8 1816.08   209.6 1809.03
   239.6 1803.35   269.6 1794.91   329.4 1788.24   359.4 1781.51   409.3 1776.85
   479.2 1768.16   549.1 1762.28   648.9 1760.65   670.9 1754.91   678.8 1753.11
   685.9 1753.44   698.8 1756.88   738.7 1777.32   748.7 1780.88   768.6 1784.93
   778.6 1785.17   828.5  1805.4   858.5 1815.86   868.4 1819.12   888.4 1822.24
   928.3  1834.6   948.3 1836.82   988.2 1837.79    1118 1850.95  1207.8 1851.49
#Mann= 3 , 0 , 0
       0     .06       0   670.9    .045       0   685.9     .06       0
Bank Sta=670.9,685.9
XS Rating Curve= 0 ,0
Exp/Cntr=0.3,0.1

Type RM Length L Ch R = 1 ,34588   ,305.2,299.9,293.5
XS GIS Cut Line= 3
     1870402.811      301909.815     1870415.598      302434.048
     1870455.164      303101.338
#Sta/Elev= 30
       0 1922.81    19.8 1921.08    29.7 1918.73    69.3 1907.34   108.8 1891.99
   118.7 1891.74   197.9 1849.32   207.8  1848.5   296.8 1807.43   316.6 1803.46
   366.1 1783.97   385.9 1778.84   405.7 1776.71   455.1 1766.28   474.9 1759.95
   504.6 1752.69   514.5 1751.79   516.9 1751.85   531.9 1752.44     694  1760.6
     714 1765.62   763.8 1781.32   783.8 1784.45   813.7 1792.53   833.7 1803.22
   843.6 1807.06   873.6 1810.15   953.4 1822.06    1133  1834.8  1192.8 1835.95
#Mann= 3 , 0 , 0
       0     .06       0   516.9    .045       0   531.9     .06       0
Bank Sta=516.9,531.9
XS Rating Curve= 0 ,0
Exp/Cntr=0.3,0.1

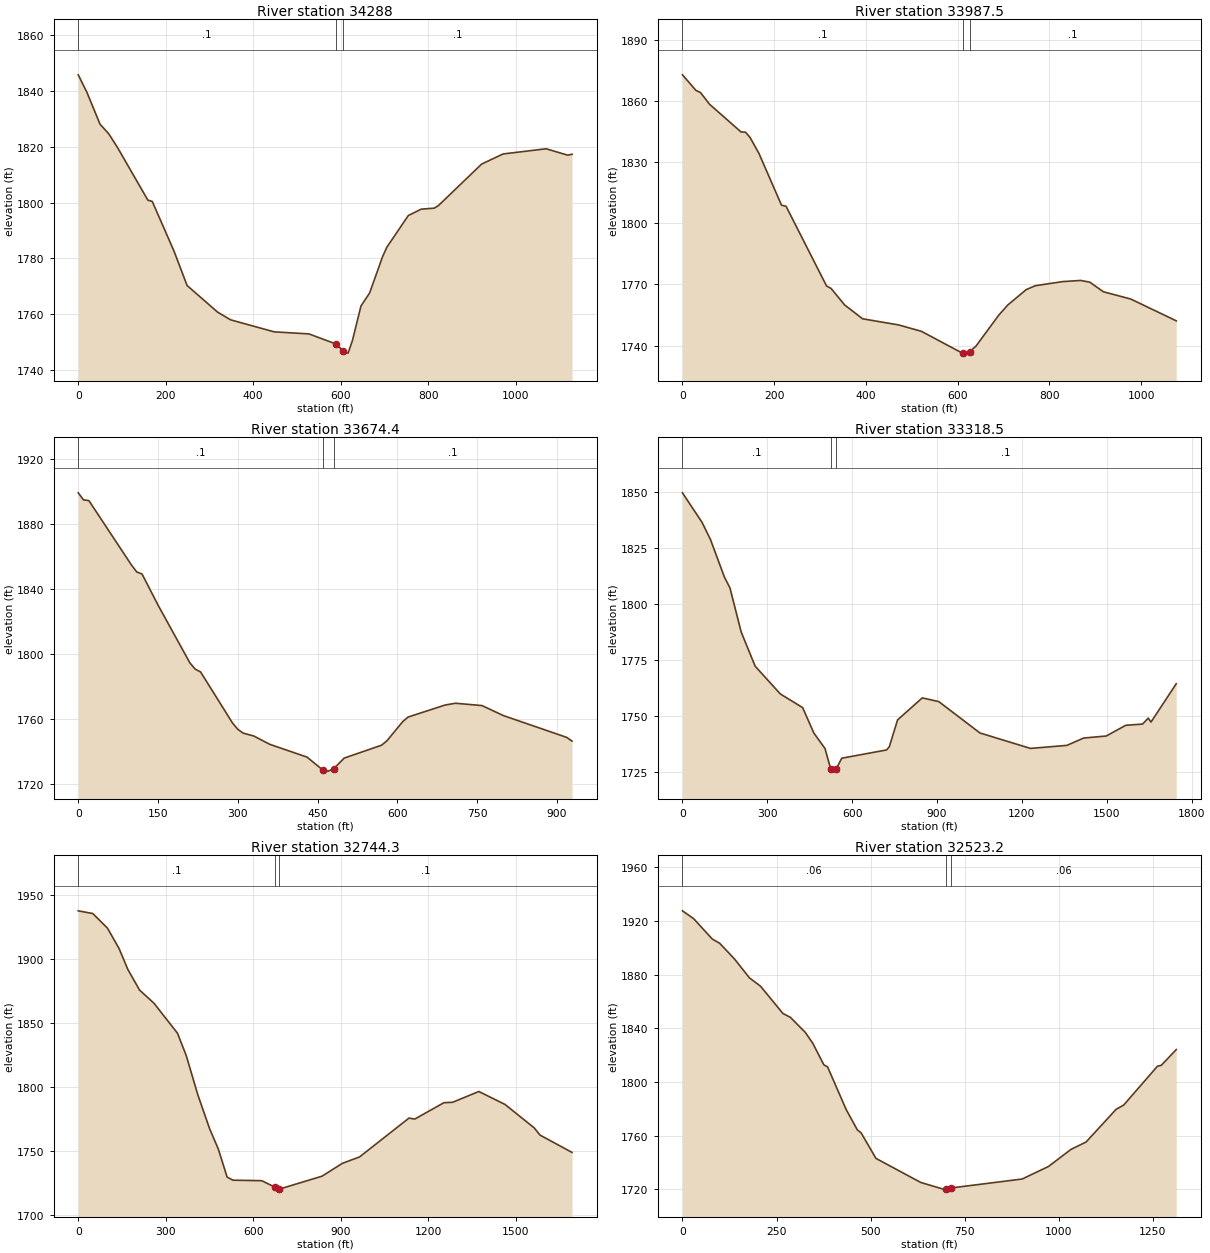
Type RM Length L Ch R = 1 ,34288   ,282.1,300.4,320.5
XS GIS Cut Line= 3
     1870026.408      302047.811     1870202.614      302618.312
     1870383.841      303118.085
#Sta/Elev= 30
       0 1845.72    19.9 1839.45    49.8 1828.05    69.7 1824.62    89.6 1819.75
   159.2 1800.85   169.2  1800.4   218.9 1782.62   248.8  1770.3   318.4 1760.78
   348.3    1758   447.8  1753.7   527.4 1752.96   589.6 1749.33   604.6 1746.98
   616.8 1746.08   626.6 1750.51   646.3 1762.96     666  1767.6   695.5 1780.54
   705.4    1784   754.6 1795.36   784.1 1797.63   813.7 1797.98   823.5 1798.93
     922 1813.76   971.2 1817.39  1069.6 1819.24  1118.9 1816.95  1128.7 1817.28
#Mann= 3 , 0 , 0
       0      .1       0   589.6    .045       0   604.6      .1       0
Bank Sta=589.6,604.6
XS Rating Curve= 0 ,0
Exp/Cntr=0.3,0.1

Type RM Length L Ch R = 1 ,33987.5 ,317.2,313.2,309.1
XS GIS Cut Line= 3
     1870001.428      301972.267     1870002.585      302443.633
     1869689.585      302961.606
#Sta/Elev= 30
       0 1872.83    29.5 1865.16    39.3 1864.16    58.9 1858.42   127.7 1844.81
   137.5 1844.68   147.3 1842.12   166.9 1834.21     216 1808.86   225.9 1808.34
   314.2 1769.22   324.1 1768.02   353.5 1759.94   392.8 1753.13   471.4 1750.12
     521 1746.99   610.3 1736.29     611 1736.32     626 1736.98     640 1739.75
   689.6 1754.92   709.5 1759.95   749.2  1767.4     769 1769.35   828.5 1771.37
   868.2 1771.96   888.1  1771.1   917.8 1766.39   977.4 1762.83  1076.6 1752.13
#Mann= 3 , 0 , 0
       0      .1       0     611    .045       0     626      .1       0
Bank Sta=611,626
XS Rating Curve= 0 ,0
Exp/Cntr=0.3,0.1

Type RM Length L Ch R = 1 ,33674.4 ,373.1,355.9,338.8
XS GIS Cut Line= 3
      1869850.51      301990.508      1869612.48      302541.568
     1869539.759      302861.722
#Sta/Elev= 30
       0 1899.01      10 1894.66      20 1894.26     100 1854.71     110 1850.41
     120 1849.13   150.1 1830.01   210.1 1794.45   220.1 1790.64   230.1 1788.94
   290.1  1757.6   300.1  1753.7   310.1 1751.35   330.2 1749.58   360.2 1744.47
   430.2 1736.62   460.2 1728.61   470.2    1728   480.2 1729.42   500.2 1736.02
   570.3 1743.91   580.3 1746.56   610.2  1758.4   620.2 1761.21   689.8 1768.61
   709.7 1769.71   759.4 1768.27   799.2 1762.17   918.6 1748.73   928.6 1746.45
#Mann= 3 , 0 , 0
       0      .1       0   460.2    .045       0   480.2      .1       0
Bank Sta=460.2,480.2
XS Rating Curve= 0 ,0
Exp/Cntr=0.3,0.1

Type RM Length L Ch R = 1 ,33318.5 ,572.8,574.1,575.4
XS GIS Cut Line= 4
     1869166.961       301835.24     1869425.345      302529.761
     1869472.555      302836.845     1869889.354      303391.664
#Sta/Elev= 30
       0 1849.41    69.2 1836.27    98.8  1828.7   148.2 1811.94     168 1807.06
   207.5 1787.49   256.9 1772.27   345.8 1759.91   424.9  1753.8   464.4 1742.51
   503.9 1735.61   523.7 1726.63   533.5 1725.54   543.4 1726.53   563.2 1731.29
   721.3 1734.96   731.2 1736.38   760.4 1748.34   847.8 1758.14   906.1 1756.49
  1051.7 1742.52  1230.2 1735.65    1359    1737  1418.5 1740.28  1497.8 1741.16
  1567.2 1745.94  1626.7 1746.49  1646.5 1749.14  1656.4 1747.38  1745.6 1764.45
#Mann= 3 , 0 , 0
       0      .1       0   523.7    .045       0   543.4      .1       0
Bank Sta=523.7,543.4
XS Rating Curve= 0 ,0
Exp/Cntr=0.3,0.1

Type RM Length L Ch R = 1 ,32744.3 ,222.9,221.1,219.6
XS GIS Cut Line= 4
     1868733.323      302041.009     1868884.754      302538.924
     1869019.777      302982.568       1869437.1      303555.363
#Sta/Elev= 30
       0    1938      50 1935.88   100.1 1924.52   140.1 1908.52   170.1 1892.19
   210.2 1876.09   260.2 1865.65   340.3 1842.33   370.3 1824.87   410.3 1793.99
   450.4  1767.7   480.4 1751.71   510.4 1729.88   530.3 1727.44     629 1727.05
   674.4 1722.01   688.2 1720.45   689.4 1720.45   836.2  1730.6   905.2 1740.58
   964.4  1745.6  1133.9 1775.97  1153.9 1775.23  1253.7 1788.01  1283.6 1788.34
  1373.4 1796.77  1463.3 1786.63  1563.1 1768.36  1583.1  1762.7  1692.9 1749.16
#Mann= 3 , 0 , 0
       0      .1       0   674.4    .045       0   689.4      .1       0
Bank Sta=674.4,689.4
XS Rating Curve= 0 ,0
Exp/Cntr=0.3,0.1

Type RM Length L Ch R = 1 ,32523.2 ,326.3,338.2,349.8
XS GIS Cut Line= 3
     1868714.446      302066.194     1868694.173      302669.032
     1868934.232      303336.065
#Sta/Elev= 30
       0 1927.45    29.7 1921.63    79.1 1906.47    98.9 1903.27   138.4 1891.57
     178 1877.53   207.6 1871.28     267    1851   286.8 1848.13   326.3 1836.96
   346.1 1828.94   375.8 1812.75   385.6 1811.25   435.1 1779.44   464.7 1764.34
   474.6 1762.16   514.2  1743.1   633.1  1725.2     693 1720.22   699.2 1720.38
   714.2  1721.1   902.7 1727.75   972.6 1737.09  1032.5 1749.83  1072.5 1755.31
  1152.3 1779.65  1172.3  1782.8  1262.2 1811.75  1272.2 1812.39  1312.1 1824.14
#Mann= 3 , 0 , 0
       0     .06       0   699.2    .045       0   714.2     .06       0
Bank Sta=699.2,714.2
XS Rating Curve= 0 ,0
Exp/Cntr=0.3,0.1

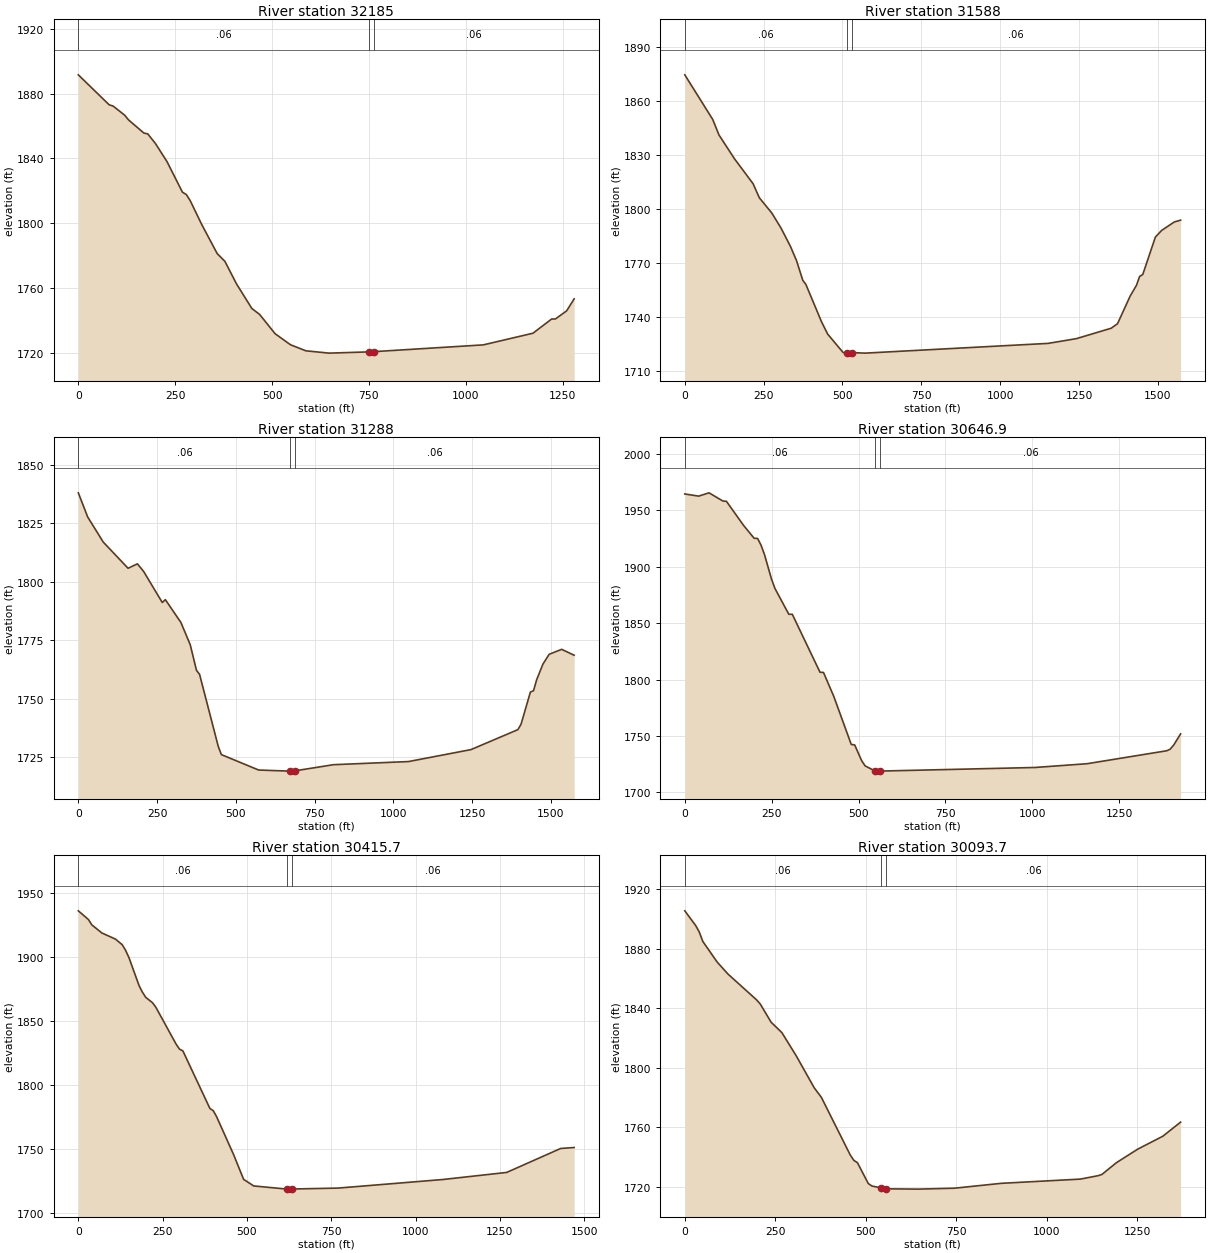
Type RM Length L Ch R = 1 ,32185   ,626.8,596.2,609.3
XS GIS Cut Line= 3
     1868631.314      302072.335     1868435.789      303180.302
     1868486.378      303326.608
#Sta/Elev= 30
       0 1891.53    79.6 1873.06    89.6 1872.32   119.5  1866.7   129.4 1863.81
   169.3 1855.64   179.2 1855.16   199.1 1849.21     229 1838.02   268.8 1819.22
   278.8 1817.79   288.7 1814.08   318.6  1799.3   358.4 1781.45   378.4 1776.63
   408.2  1762.8     448 1747.57     468 1743.93   507.8  1732.1   547.6 1725.26
   587.4 1721.53   647.2  1720.1   749.4 1720.86   764.4 1721.03  1045.4 1725.18
  1173.5 1732.36  1221.8 1741.11  1231.5 1741.14  1260.5 1746.14  1279.9 1753.52
#Mann= 3 , 0 , 0
       0     .06       0   749.4    .045       0   764.4     .06       0
Bank Sta=749.4,764.4
XS Rating Curve= 0 ,0
Exp/Cntr=0.3,0.1

Type RM Length L Ch R = 1 ,31588   ,293.3,298.2,297.8
XS GIS Cut Line= 3
     1868578.352      302019.035     1868288.541      302452.964
     1867765.091      303363.553
#Sta/Elev= 30
       0 1874.51    88.6 1849.68   108.3  1841.1   157.5 1827.84   216.6 1813.94
   236.3 1806.14   275.7  1797.7   305.2 1789.25   334.8 1779.18   354.4 1771.13
   374.1 1760.23     384 1757.93   433.2  1737.3   452.9 1730.35   502.1 1720.06
   514.3 1719.84   529.3 1720.02   571.8 1719.74    1152 1725.16    1242 1727.81
  1352.1  1733.6  1372.1 1736.12  1412.1 1751.46  1432.1 1757.46  1442.1 1762.39
  1452.1 1763.47  1492.1  1784.3  1512.1 1788.01  1552.1 1792.69  1572.1 1793.69
#Mann= 3 , 0 , 0
       0     .06       0   514.3    .045       0   529.3     .06       0
Bank Sta=514.3,529.3
XS Rating Curve= 0 ,0
Exp/Cntr=0.3,0.1

Type RM Length L Ch R = 1 ,31288   ,661.8,641.7,628.1
XS GIS Cut Line= 3
     1868392.101      301919.265     1868008.789       302482.26
     1867620.323      303286.587
#Sta/Elev= 30
       0 1838.04    29.6 1827.74      79 1816.99   157.9 1805.77   187.6 1807.66
   207.3 1804.42   266.5 1791.13   276.4 1792.34   325.7 1782.58   355.4 1773.02
   375.1 1762.14     385 1760.37   444.2 1729.61   454.1 1726.06   572.5 1719.46
   671.2 1718.99   673.6 1718.99   688.6 1719.14   810.1 1721.74  1048.3 1723.08
  1246.8  1728.2  1395.7 1736.74  1405.6 1739.04  1435.4 1752.82  1445.3 1753.38
  1455.2 1758.07  1475.1 1764.76  1494.9 1768.97  1534.6 1771.09  1574.3 1768.57
#Mann= 3 , 0 , 0
       0     .06       0   673.6    .045       0   688.6     .06       0
Bank Sta=673.6,688.6
XS Rating Curve= 0 ,0
Exp/Cntr=0.3,0.1

Type RM Length L Ch R = 1 ,30646.9 ,225.8,231.2,236.5
XS GIS Cut Line= 2
     1867650.818      301729.972     1867671.633      303156.479
#Sta/Elev= 30
       0 1964.54    39.9 1962.64    69.8 1965.56   109.7 1958.27   119.7 1958.07
   169.6  1936.5   199.5  1925.3   209.5 1925.11   219.5 1919.11   229.5 1910.66
   249.4 1889.22   259.4 1880.82   299.3 1857.93   309.3 1857.93   389.1 1806.55
   399.1 1806.35     429 1784.92   478.9  1742.6   488.9 1742.11   508.8 1728.25
   518.8 1723.59   546.9 1719.13   558.7 1718.92   561.9 1718.96  1007.6 1722.15
  1157.3 1725.48  1386.8 1736.97  1396.7  1738.4  1406.7 1742.01  1426.7 1751.94
#Mann= 3 , 0 , 0
       0     .06       0   546.9    .045       0   561.9     .06       0
Bank Sta=546.9,561.9
XS Rating Curve= 0 ,0
Exp/Cntr=0.3,0.1

Type RM Length L Ch R = 1 ,30415.7 ,316.6,321.4,322.3
XS GIS Cut Line= 3
     1867568.729      301727.008     1867317.959      302982.391
     1867295.968      303171.139
#Sta/Elev= 30
       0 1935.74      30 1928.94      40 1924.79      70 1918.45     110 1913.71
     130 1909.38     140 1905.03     150 1899.37     180 1877.53     190 1872.33
     200 1868.28     220 1864.11     230 1860.52     290 1831.81     300 1827.94
     310 1826.58   390.1 1781.72   400.1 1779.96   410.1 1775.25   460.1 1745.92
   490.1 1726.44   520.1  1721.3     619 1718.84   620.1 1718.82     634 1718.91
   770.1 1719.63  1080.2  1726.3  1270.2 1731.84  1430.2 1750.51  1470.2 1751.26
#Mann= 3 , 0 , 0
       0     .06       0     619    .045       0     634     .06       0
Bank Sta=619,634
XS Rating Curve= 0 ,0
Exp/Cntr=0.3,0.1

Type RM Length L Ch R = 1 ,30093.7 ,305,306,310.1
XS GIS Cut Line= 3
     1867513.408      301698.388     1866966.117      302745.997
     1866870.826      302907.258
#Sta/Elev= 30
       0  1905.3    29.8 1895.53    39.7 1891.26    49.7  1884.8    89.4 1870.94
   119.2 1862.89   198.6 1845.49   208.6  1842.7   238.4 1830.58   268.2 1823.57
   307.9 1807.97   357.6  1786.5   377.4 1780.09   456.9 1741.51   466.8 1737.91
   476.8 1736.33   506.6 1722.39   516.5 1720.69     541 1719.47     556  1718.8
   645.6 1718.59   744.9 1719.22     874 1722.48  1092.6 1725.32  1142.2 1727.65
  1152.2 1728.48  1191.8  1736.3    1251 1745.44    1320 1754.06  1369.3 1763.54
#Mann= 3 , 0 , 0
       0     .06       0     541    .045       0     556     .06       0
Bank Sta=541,556
XS Rating Curve= 0 ,0
Exp/Cntr=0.3,0.1

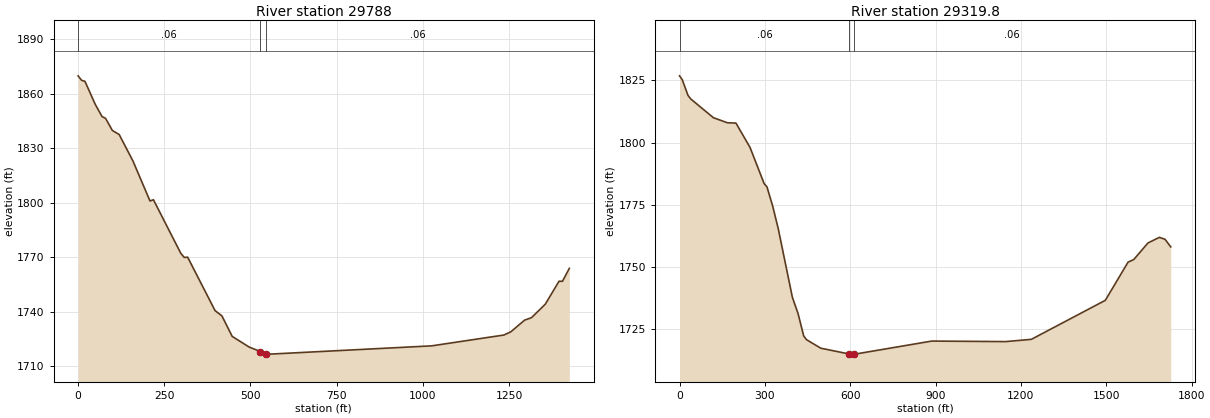
Type RM Length L Ch R = 1 ,29788   ,466.3,468,468.2
XS GIS Cut Line= 3
     1867193.508      301533.109     1867005.186      302035.338
     1866695.246      302868.073
#Sta/Elev= 30
       0 1869.72     9.9  1867.3    19.9 1866.68    49.7 1854.06    69.5 1847.32
    79.5 1846.37    99.3  1839.7   119.2 1837.44   158.9 1822.97   208.6 1800.89
   218.5 1801.59     298 1772.09   307.9 1769.87   317.8 1769.99   397.3 1740.62
   417.2 1737.71     447 1726.44   496.6 1720.53   528.9 1718.13   543.9 1716.91
   556.3 1716.69  1025.6 1721.24  1235.2 1727.19  1255.2 1728.96  1295.1 1735.37
  1315.1 1736.73    1355 1744.11    1395 1756.77    1405 1756.73  1424.9 1763.85
#Mann= 3 , 0 , 0
       0     .06       0   528.9    .045       0   543.9     .06       0
Bank Sta=528.9,543.9
XS Rating Curve= 0 ,0
Exp/Cntr=0.3,0.1

Type RM Length L Ch R = 1 ,29319.8 ,632.7,623,613.3
XS GIS Cut Line= 3
     1866839.403      301431.691     1866702.576      301793.306
     1866262.774      303058.959
#Sta/Elev= 30
       0 1826.87     9.9 1825.24    29.7 1819.02    39.6 1817.56     119 1810.03
   168.5 1807.98   198.3 1807.86   247.8 1798.08   297.4 1783.51   307.3 1782.21
   327.2 1774.58     347 1765.39   396.6 1737.81   416.6 1731.23   436.6 1722.19
   446.6 1720.71   496.6 1717.29   597.2 1714.95   612.2 1714.92   616.6 1714.91
   886.6 1720.16  1146.6 1719.95  1236.6 1720.86  1496.5 1736.55  1576.5 1751.92
  1596.5 1752.96  1646.5 1759.64  1686.5 1761.88  1706.5  1761.1  1726.5 1758.05
#Mann= 3 , 0 , 0
       0     .06       0   597.2    .045       0   612.2     .06       0
Bank Sta=597.2,612.2
XS Rating Curve= 0 ,0
Exp/Cntr=0.3,0.1