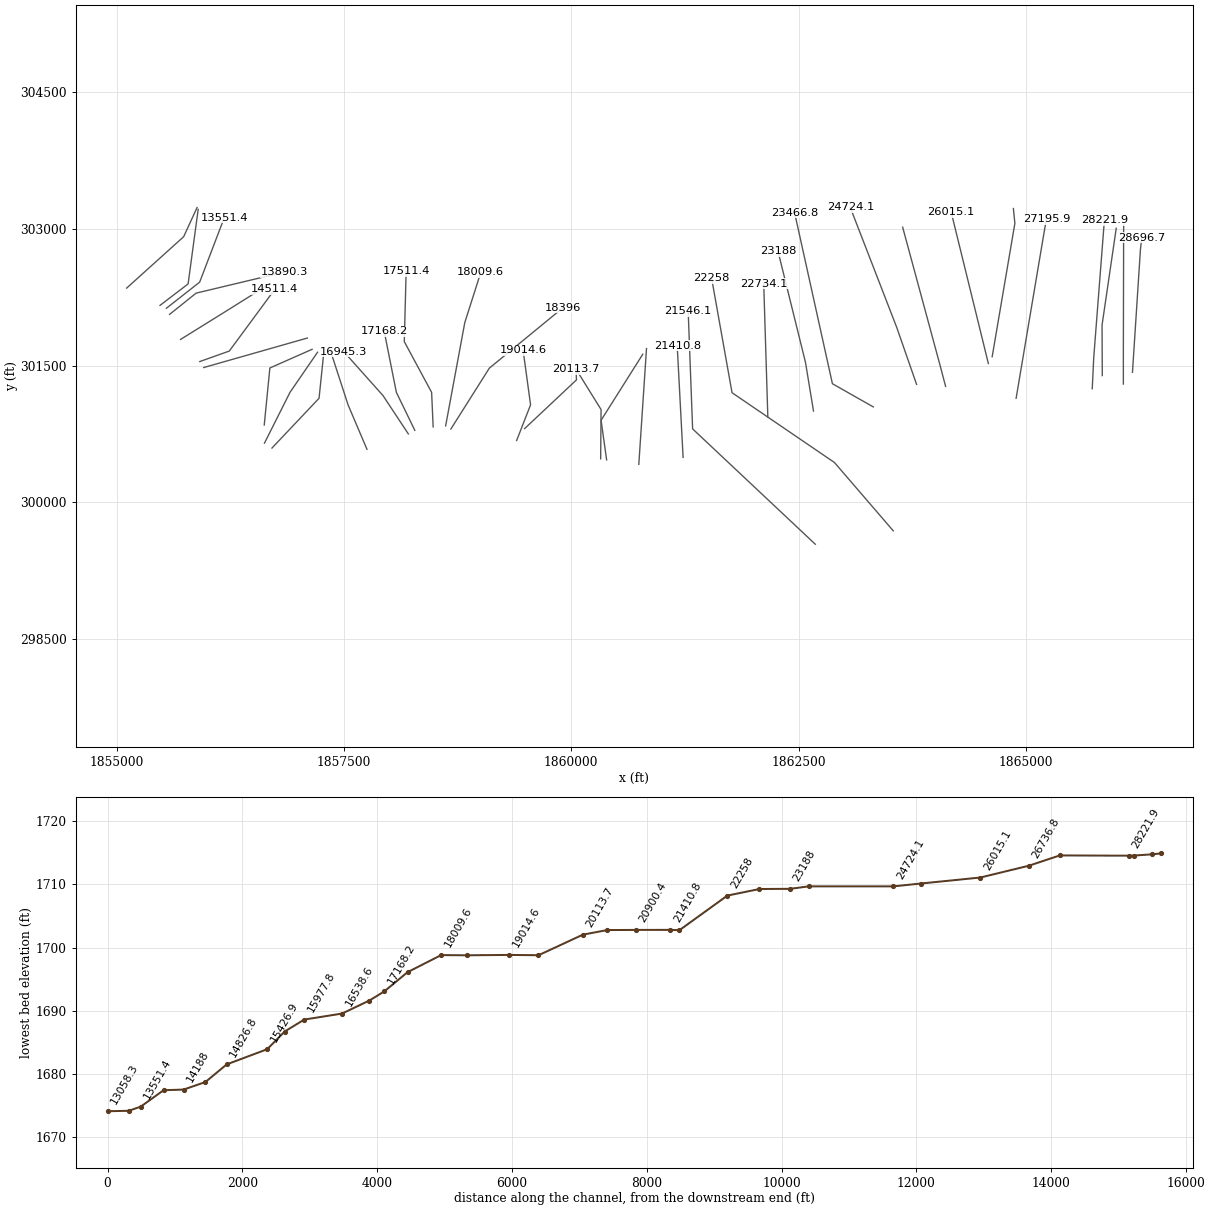
HEC-RAS study SndlckCrk.prj: SndlckCrk

--- SndlckCrk.g01 (geometry) --- (continued)

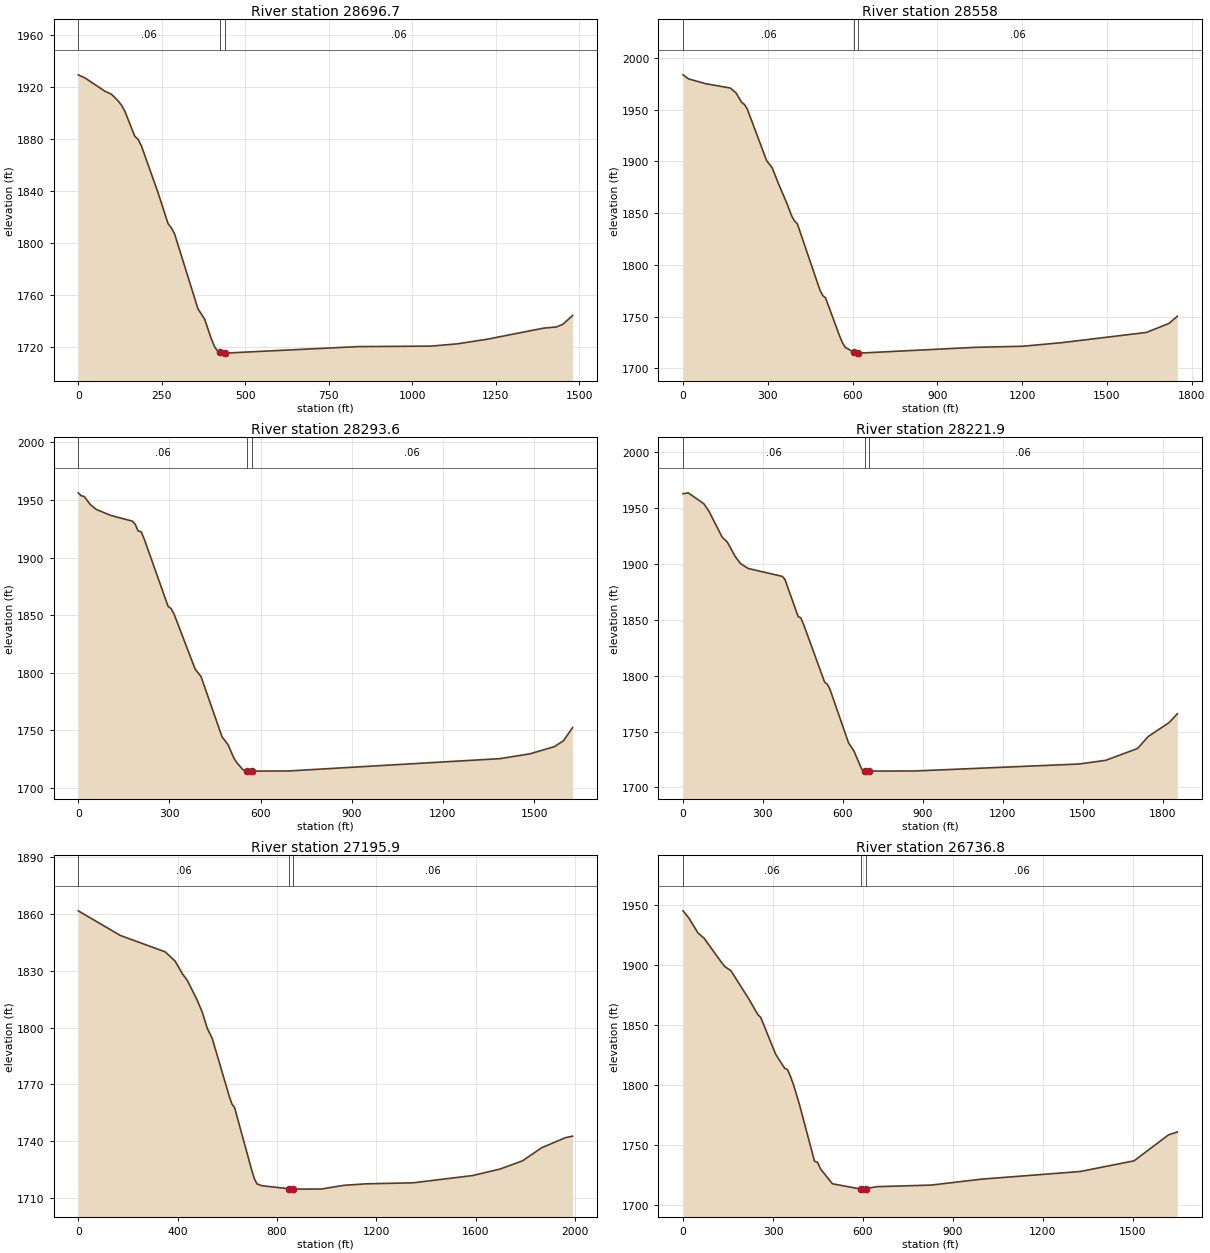
Type RM Length L Ch R = 1 ,28696.7 ,135.1,138.6,142.2
XS GIS Cut Line= 3
      1866172.37      301426.804      1866260.33      302777.974
      1866274.99      302902.585
#Sta/Elev= 30
       0 1929.18    19.9 1926.85    79.6 1916.57    99.6 1914.22   119.5 1909.08
   129.4 1905.77   139.4  1901.2   169.2 1881.88   179.2 1879.52   189.2 1874.39
     239 1838.29   268.8 1814.61   278.8 1811.36   288.7 1806.44   358.4 1748.94
   378.3 1741.08   398.2 1725.93   408.2 1719.78   418.2 1716.14   423.9 1715.47
   438.1 1714.92   438.9 1714.93   836.3 1719.93  1055.4 1720.31    1135 1722.09
  1224.6 1725.65  1392.6 1734.15  1431.2 1735.07  1450.6 1737.13  1479.5 1743.87
#Mann= 3 , 0 , 0
       0     .06       0   423.9    .045       0   438.9     .06       0
Bank Sta=423.9,438.9
XS Rating Curve= 0 ,0
Exp/Cntr=0.3,0.1

Type RM Length L Ch R = 1 ,28558   ,270.5,262.9,251.3
XS GIS Cut Line= 3
     1866072.193      301297.714     1866072.193      301662.587
     1866075.451       303047.15
#Sta/Elev= 30
       0 1983.53    19.7 1979.59    78.9 1975.04   167.6 1970.76   187.4 1966.14
   207.1 1957.09     217  1954.9   226.8 1950.88   295.8 1900.69   315.6 1893.72
   335.3 1880.04   364.9 1861.13   384.8 1847.11   394.8 1842.26   404.7 1839.54
   484.4 1775.72   494.4 1770.42   504.3 1768.14   554.1 1731.38   564.1 1724.91
     574  1720.4   603.7  1715.7   618.7 1714.79   623.9 1714.77  1032.2 1720.35
  1201.6  1721.4    1341  1724.9  1639.9 1734.75  1719.6 1743.43  1749.4  1750.4
#Mann= 3 , 0 , 0
       0     .06       0   603.7    .045       0   618.7     .06       0
Bank Sta=603.7,618.7
XS Rating Curve= 0 ,0
Exp/Cntr=0.3,0.1

Type RM Length L Ch R = 1 ,28293.6 ,69.5,73.2,80.8
XS GIS Cut Line= 3
     1865840.489      301390.631     1865837.695      301942.562
     1865993.864      303005.999
#Sta/Elev= 30
       0 1956.21     9.9 1953.66    19.7 1953.03    39.4 1946.13    59.1 1941.81
   108.4 1936.48   177.4 1931.67   187.3 1928.99   197.1  1923.1     207 1922.43
   216.8 1916.35   295.7 1857.62   305.5 1855.79   315.4  1850.9   384.4 1803.32
   404.1 1796.66   473.1  1744.4   492.8  1737.6   512.5  1725.7   522.4 1721.76
   542.1 1715.78   556.3 1714.61   561.9 1714.58   571.3  1714.6   691.3 1714.71
  1387.9 1725.42  1487.4 1729.66  1567.1 1735.85  1596.9 1740.96  1626.8 1752.39
#Mann= 3 , 0 , 0
       0     .06       0   556.3    .045       0   571.3     .06       0
Bank Sta=556.3,571.3
XS Rating Curve= 0 ,0
Exp/Cntr=0.3,0.1

Type RM Length L Ch R = 1 ,28221.9 ,1022.6,1025.8,1029.3
XS GIS Cut Line= 3
     1865730.124      301245.589     1865746.413      301587.658
     1865863.694      303096.017
#Sta/Elev= 30
       0 1962.68    19.6 1963.51    78.3 1953.69    97.8 1946.81   146.8 1923.89
   166.3 1919.42   195.7 1906.64   215.3 1900.32   244.6 1895.82   372.3 1888.79
   382.3  1886.2     432 1852.89     442  1851.6   451.9 1846.19   531.6 1794.04
   541.5 1792.29   551.5 1787.76   621.2 1739.85   641.1 1732.77   670.9 1716.16
   680.9 1714.56   681.8 1714.56   696.8  1714.6     870 1714.69  1487.1 1720.93
  1586.6 1724.22  1706.1 1734.84  1745.9 1745.51  1825.5 1758.15  1855.4 1765.88
#Mann= 3 , 0 , 0
       0     .06       0   681.8    .045       0   696.8     .06       0
Bank Sta=681.8,696.8
XS Rating Curve= 0 ,0
Exp/Cntr=0.3,0.1

Type RM Length L Ch R = 1 ,27195.9 ,458.3,458.4,454.9
XS GIS Cut Line= 3
     1864892.871       301141.34     1865195.846      302933.127
     1865225.166      303102.532
#Sta/Elev= 30
       0 1861.66   169.7 1848.62   349.5 1840.01   389.4 1835.17   419.4 1828.32
   439.3 1824.83   479.3 1814.28   499.2 1808.01   519.2 1799.58   539.2  1794.2
   609.1 1763.05     619 1759.45     629 1757.73   698.9 1724.28   708.9 1720.08
   718.9 1717.42   738.9 1716.39   847.5 1714.83   862.5 1714.62   868.7  1714.6
   978.5 1714.65  1068.4  1716.6  1158.2  1717.4  1347.9 1717.94  1587.6 1721.78
  1697.4 1725.22  1787.3 1729.51    1865 1736.48  1960.5 1741.78  1989.2  1742.6
#Mann= 3 , 0 , 0
       0     .06       0   847.5    .045       0   862.5     .06       0
Bank Sta=847.5,862.5
XS Rating Curve= 0 ,0
Exp/Cntr=0.3,0.1

Type RM Length L Ch R = 1 ,26736.8 ,713.6,721.2,727.7
XS GIS Cut Line= 3
     1864629.472      301596.701     1864879.248      303059.931
     1864862.959      303222.821
#Sta/Elev= 30
       0 1945.33    19.9  1939.1    49.8 1926.81    69.7 1922.63   129.5 1901.84
   139.5 1898.73   159.4  1895.4   219.2 1871.82   249.1 1858.76     259 1856.37
   308.8 1825.62   338.7 1813.92   348.7 1812.73   358.6 1806.82   368.6 1799.93
   388.5 1783.25   438.3 1736.31   448.3  1735.4   458.3  1729.9   498.1 1717.43
   593.5 1712.98   597.7 1712.97   608.5 1713.49   647.6 1715.04   826.9 1716.34
   996.2 1721.31    1325 1727.71  1503.6 1736.59  1619.2 1758.37  1648.1 1760.68
#Mann= 3 , 0 , 0
       0     .06       0   593.5    .045       0   608.5     .06       0
Bank Sta=593.5,608.5
XS Rating Curve= 0 ,0
Exp/Cntr=0.3,0.1

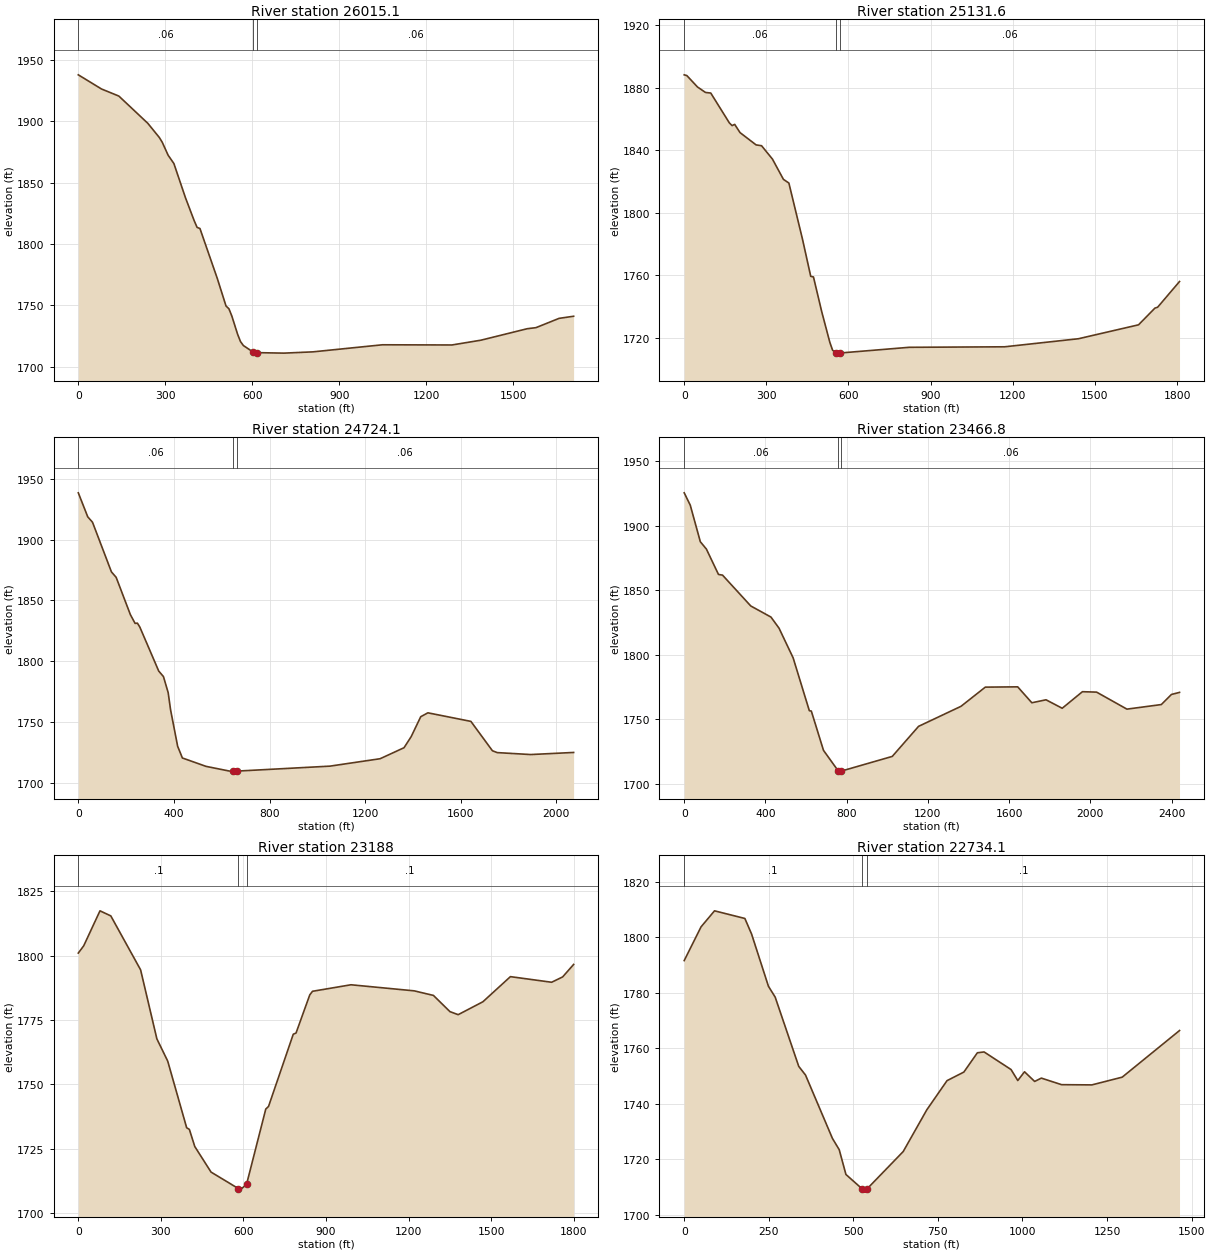
Type RM Length L Ch R = 1 ,26015.1 ,881.1,883.1,885.2
XS GIS Cut Line= 2
     1864587.694      301522.471     1864179.414      303180.719
#Sta/Elev= 30
       0 1937.84    79.9 1926.31   139.8 1920.53   239.7 1898.33   279.6 1886.72
   289.6 1882.83   309.6 1872.39   329.6 1865.54   369.5 1837.69   399.5 1819.05
   409.5 1813.57   419.4 1812.63   479.4 1771.84   509.3 1749.49   519.3 1747.25
   529.3 1741.37   549.3 1726.46   559.3 1720.49   569.3 1717.26   601.5 1712.16
   616.5 1711.49   709.1  1711.1   808.9 1712.13  1048.6 1717.89  1288.3 1717.74
  1388.2 1721.64    1548 1730.99  1577.9 1731.85  1657.8 1739.43  1707.8 1741.15
#Mann= 3 , 0 , 0
       0     .06       0   601.5    .045       0   616.5     .06       0
Bank Sta=601.5,616.5
XS Rating Curve= 0 ,0
Exp/Cntr=0.3,0.1

Type RM Length L Ch R = 1 ,25131.6 ,405.6,406.9,408.8
XS GIS Cut Line= 3
     1864117.516      301271.651     1864055.618      301506.213
     1863645.135       303017.83
#Sta/Elev= 30
       0 1888.34     9.7 1887.85    48.5 1880.56    77.6 1877.07      97 1876.67
     165 1857.54   174.7 1855.84   184.4 1856.61   203.8 1851.36   262.5 1843.48
   282.5 1842.95   322.4 1834.36   362.3 1821.43   382.3 1819.04   432.2 1782.95
   462.1 1759.32   472.1 1758.91     502 1736.86   531.9 1717.02   541.9 1712.06
     553  1710.3   561.8 1710.15     568 1710.21   821.2 1713.87  1170.4  1714.2
  1439.8 1719.36  1659.3 1728.27  1719.2 1738.97  1729.1 1739.55    1809    1756
#Mann= 3 , 0 , 0
       0     .06       0     553    .045       0     568     .06       0
Bank Sta=553,568
XS Rating Curve= 0 ,0
Exp/Cntr=0.3,0.1

Type RM Length L Ch R = 1 ,24724.1 ,1253.5,1254.6,1250.3
XS GIS Cut Line= 3
     1863798.077      301294.307     1863579.396      301920.391
     1863069.222      303234.169
#Sta/Elev= 30
       0 1938.48    39.6 1918.72    59.4 1914.32   138.6  1873.5   158.4    1869
   217.8 1838.39   237.6 1831.17   247.4 1831.33   257.4 1828.14   336.5 1791.97
   356.3 1787.41   376.1 1774.16     386 1760.18   415.7 1730.12   435.5 1720.51
   534.5 1713.61   633.5  1709.7   647.7  1709.7   662.7  1709.7    1053  1713.8
  1262.9  1719.9  1362.9 1728.94  1392.8 1738.04  1432.8 1754.43  1462.8 1757.63
  1642.7 1750.59  1732.7 1726.47  1752.7 1724.93  1892.6 1723.33  2072.5 1725.05
#Mann= 3 , 0 , 0
       0     .06       0   647.7    .045       0   662.7     .06       0
Bank Sta=647.7,662.7
XS Rating Curve= 0 ,0
Exp/Cntr=0.3,0.1

Type RM Length L Ch R = 1 ,23466.8 ,303.7,278.7,254.9
XS GIS Cut Line= 3
      1863322.24      301046.797       1862872.7      301301.022
     1862456.515      303178.016
#Sta/Elev= 30
       0 1925.34    29.8 1915.78    79.4 1887.44   109.2 1881.77   168.8 1862.09
   188.7 1861.58   327.7 1837.68   427.1 1829.08   466.8  1820.5   536.4 1797.47
   616.1 1756.53     626 1756.23   685.8 1725.82   759.2 1709.71   765.5  1709.7
   774.2 1709.76  1024.5  1721.1    1154 1744.39  1363.2 1759.94  1482.7 1774.78
  1642.1 1775.01  1711.8 1762.67  1781.6 1764.97  1861.3 1758.41  1960.9 1771.24
  2030.6 1770.92    2180 1757.74  2349.4 1761.28  2399.2 1769.11    2439 1770.71
#Mann= 3 , 0 , 0
       0     .06       0   759.2    .045       0   774.2     .06       0
Bank Sta=759.2,774.2
XS Rating Curve= 0 ,0
Exp/Cntr=0.3,0.1

Type RM Length L Ch R = 1 ,23188   ,454.4,453.4,471.8
XS GIS Cut Line= 3
     1862664.661      301001.391     1862576.456      301535.635
     1862273.604      302757.206
#Sta/Elev= 30
       0 1801.05    19.7 1803.89    78.8 1817.47   118.1  1815.5   226.4 1794.54
   285.5 1767.72   324.9 1759.07   393.8 1733.16   403.6 1732.53   423.3 1725.86
   482.4 1715.93   581.4 1709.55   591.4 1709.31   611.4 1711.16   681.3 1740.43
   691.3 1741.45   781.2 1769.52   791.2 1769.96   841.1 1784.78   851.1  1786.2
     991 1788.73  1220.7 1786.37  1290.6 1784.59  1350.6 1778.29  1380.5 1777.11
  1470.4 1782.13  1570.3 1791.89  1720.1 1789.71  1760.1 1791.78    1800 1796.63
#Mann= 3 , 0 , 0
       0      .1       0   581.4    .045       0   611.4      .1       0
Bank Sta=581.4,611.4
XS Rating Curve= 0 ,0
Exp/Cntr=0.3,0.1

Type RM Length L Ch R = 1 ,22734.1 ,472.3,475.6,478.8
XS GIS Cut Line= 2
      1862162.52      300935.375     1862117.229      302398.849
#Sta/Elev= 30
       0 1791.61    49.8 1803.77    89.6 1809.54   179.3 1806.79   199.2 1801.17
     249 1782.36   268.9 1778.46   338.6  1753.5   358.6 1750.38   438.3 1727.52
   458.2  1723.5   478.1 1714.56   525.5 1709.43   537.9 1709.28   540.5 1709.36
   647.4 1722.82   717.2 1737.86   776.9 1748.36   826.7 1751.45   866.6  1758.4
   886.5  1758.7   966.2 1752.36   986.1  1748.4    1006 1751.56  1035.9 1748.08
  1055.8 1749.27  1115.6 1746.91  1205.2 1746.83  1294.8 1749.62  1464.2 1766.41
#Mann= 3 , 0 , 0
       0      .1       0   525.5    .045       0   540.5      .1       0
Bank Sta=525.5,540.5
XS Rating Curve= 0 ,0
Exp/Cntr=0.3,0.1

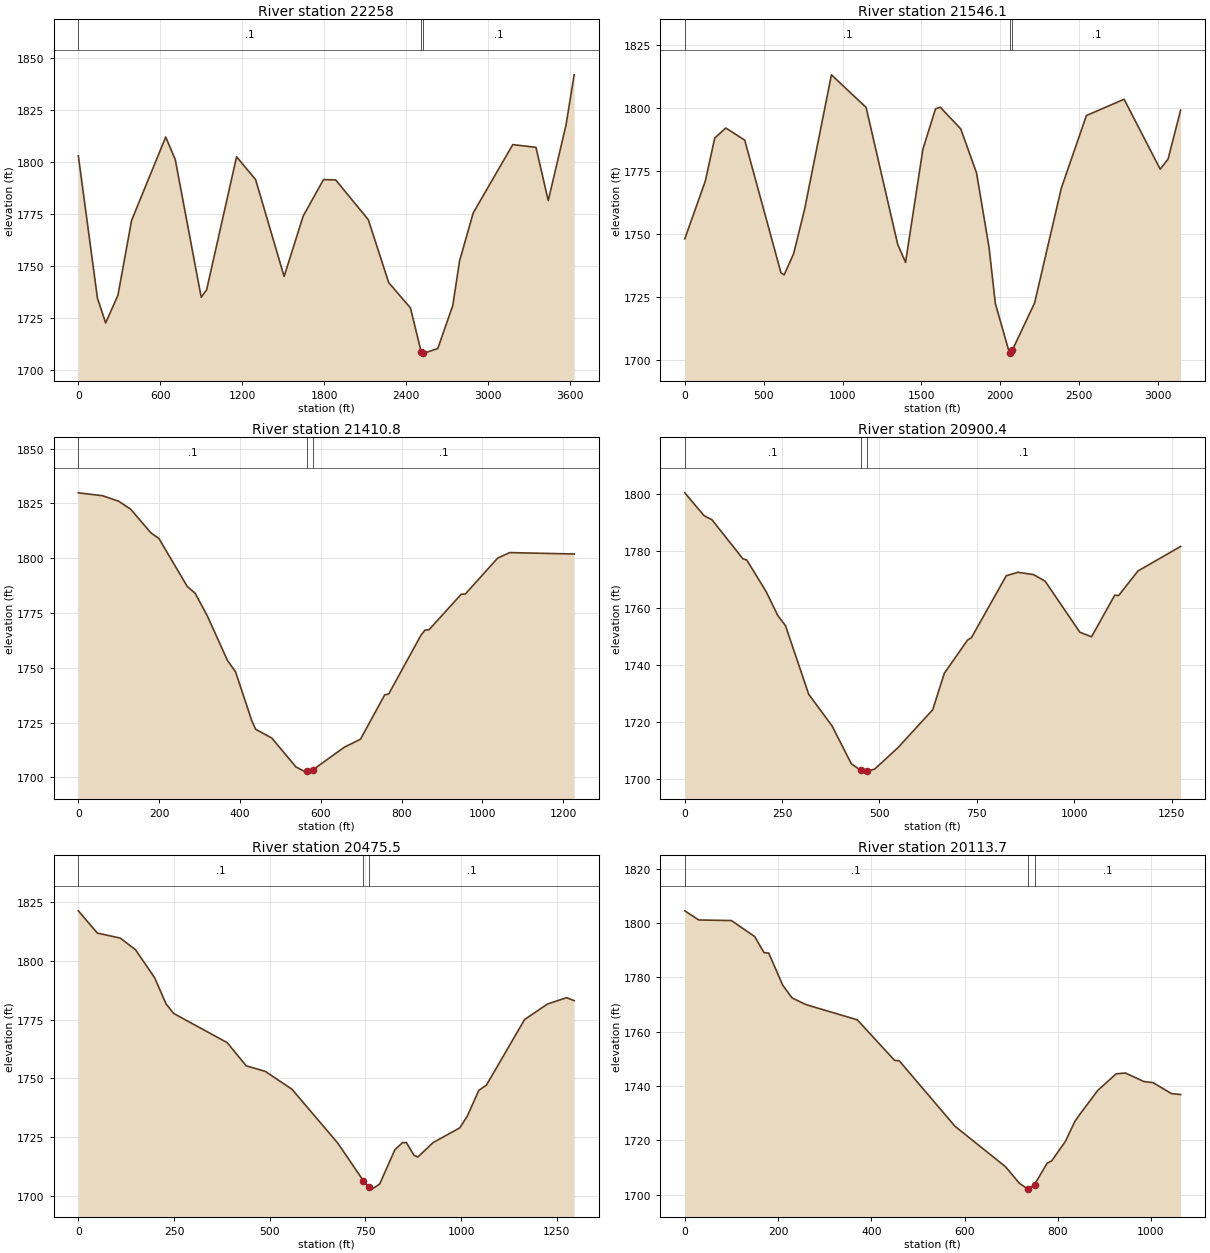
Type RM Length L Ch R = 1 ,22258   ,711.9,711.2,708.5
XS GIS Cut Line= 4
     1863541.841      299687.618     1862895.367      300436.751
     1861768.893      301202.531     1861543.857      302460.747
#Sta/Elev= 30
       0 1803.06   139.9 1734.68   199.9 1722.75   289.9 1736.02   389.8 1771.96
   639.7  1812.1   709.6 1801.23   899.6 1735.09   939.5 1738.71  1158.5 1802.57
  1297.7 1791.63  1506.5 1745.08  1645.7 1774.04  1794.8 1791.62  1884.3 1791.45
    2123 1772.33  2272.1 1742.13  2431.5 1729.94  2509.7 1708.91  2524.7 1708.39
  2531.4 1708.24  2631.2 1710.42  2741.1 1731.07    2791 1752.55  2890.9  1775.6
  3180.4 1808.42  3350.2 1807.11  3440.1 1781.54  3569.9  1817.7  3629.8 1841.95
#Mann= 3 , 0 , 0
       0      .1       0  2509.7    .045       0  2524.7      .1       0
Bank Sta=2509.7,2524.7
XS Rating Curve= 0 ,0
Exp/Cntr=0.3,0.1

Type RM Length L Ch R = 1 ,21546.1 ,133.5,134.9,136.3
XS GIS Cut Line= 3
       1862684.5      299540.566     1861335.359      300805.787
     1861286.492      302099.131
#Sta/Elev= 30
       0 1748.02     130  1770.9     190 1787.97   259.9 1791.94   379.9 1787.14
   609.9 1734.56   629.9 1733.77   689.8 1742.09   759.8 1759.77   929.8    1813
  1149.7 1800.08  1349.7 1745.89  1399.7 1738.69  1509.7 1783.52  1589.6 1799.53
  1619.6 1800.19  1749.6 1791.59  1849.6 1774.19  1929.2  1744.6  1969.1 1722.39
  2058.7 1702.76  2062.2 1702.87  2077.2 1703.99    2218 1722.63  2387.2 1768.06
  2546.5 1796.88  2785.4 1803.32  3014.4 1775.62  3064.2 1779.65  3143.8    1799
#Mann= 3 , 0 , 0
       0      .1       0  2062.2    .045       0  2077.2      .1       0
Bank Sta=2062.2,2077.2
XS Rating Curve= 0 ,0
Exp/Cntr=0.3,0.1

Type RM Length L Ch R = 1 ,21410.8 ,514.4,510.6,506.6
XS GIS Cut Line= 2
     1861230.739      300492.898     1861165.953      301717.969
#Sta/Elev= 30
       0 1829.84    59.8 1828.52    99.7 1826.02   129.7 1822.32   179.5 1811.58
   199.5 1808.97   269.3 1787.17   289.2 1783.95   319.2 1773.65     369 1753.33
     389 1748.15   428.9 1725.98   438.8 1721.89   478.7 1717.91   538.6 1704.69
   558.5 1702.81     565 1702.81     580 1703.37   658.3 1713.75   698.2 1717.39
     758 1737.62     768 1738.04   847.8 1764.85   857.8 1767.18   867.7 1767.34
   947.5 1783.58   957.5 1783.64  1037.3 1800.01  1067.2 1802.56  1226.8 1801.91
#Mann= 3 , 0 , 0
       0      .1       0     565    .045       0     580      .1       0
Bank Sta=565,580
XS Rating Curve= 0 ,0
Exp/Cntr=0.3,0.1

Type RM Length L Ch R = 1 ,20900.4 ,434.5,425,414.4
XS GIS Cut Line= 2
     1860743.656      300416.659     1860828.359        301687.2
#Sta/Elev= 30
       0 1800.32    49.7 1792.28    69.6 1790.91   149.2 1777.21   159.2 1776.77
   208.9 1765.71   238.8 1757.33   258.6 1753.78   318.3 1729.71     378 1718.69
   427.8 1705.35   452.5 1703.05   457.6  1702.8   467.5  1702.8   487.5  1703.5
   547.2 1710.98   636.7 1724.31   666.5 1737.09   726.2 1748.72   736.2 1749.56
   825.7 1771.27   855.5 1772.48   895.3 1771.68   925.2  1769.4  1014.7 1751.46
  1044.6 1749.88  1104.2 1764.46  1114.2 1764.34  1163.9 1772.94  1273.4 1781.53
#Mann= 3 , 0 , 0
       0      .1       0   452.5    .045       0   467.5      .1       0
Bank Sta=452.5,467.5
XS Rating Curve= 0 ,0
Exp/Cntr=0.3,0.1

Type RM Length L Ch R = 1 ,20475.5 ,337.8,361.7,386.8
XS GIS Cut Line= 3
      1860389.86      300465.851       1860328.7      300900.263
     1860787.055      301624.287
#Sta/Elev= 30
       0 1821.43    49.8 1811.93   109.7 1809.81   149.6  1804.8   199.4 1792.89
   229.3 1781.72   249.3 1777.66   388.8 1765.25   438.7 1755.35   488.5 1752.98
   558.3 1745.36   677.8 1722.44   744.7 1706.39   759.7 1703.49   767.5 1702.78
   787.4 1704.96   827.3  1719.6   847.2 1722.61   857.2 1722.62   877.1  1717.2
   887.1 1716.47   926.9 1722.61   996.7  1728.9  1016.6 1733.97  1046.5 1744.89
  1066.4 1747.14  1166.1 1775.09  1225.9  1781.7  1275.7  1784.4  1295.6 1783.15
#Mann= 3 , 0 , 0
       0      .1       0   744.7    .045       0   759.7      .1       0
Bank Sta=744.7,759.7
XS Rating Curve= 0 ,0
Exp/Cntr=0.3,0.1

Type RM Length L Ch R = 1 ,20113.7 ,690.1,659.1,627.9
XS GIS Cut Line= 3
     1860324.063      300477.582       1860328.7      301017.543
      1860052.24      301462.284
#Sta/Elev= 30
       0 1804.51      30 1801.14     100 1800.93     150 1795.02     170  1789.1
     180 1788.98     210 1777.15     230 1772.46     260 1769.98     370 1764.38
     450 1749.46     460 1749.31   579.5 1725.21   688.2 1710.26   717.8 1704.18
   735.2 1702.18   737.6 1702.05   750.2 1703.72   777.1 1711.56     787 1712.46
   816.6 1719.66   836.4 1726.88   846.3 1729.34   885.8 1738.38   925.3  1744.5
   945.1  1744.8   984.6 1741.68  1004.4 1741.25  1043.9 1737.23  1063.6 1736.87
#Mann= 3 , 0 , 0
       0      .1       0   735.2    .045       0   750.2      .1       0
Bank Sta=735.2,750.2
XS Rating Curve= 0 ,0
Exp/Cntr=0.3,0.1

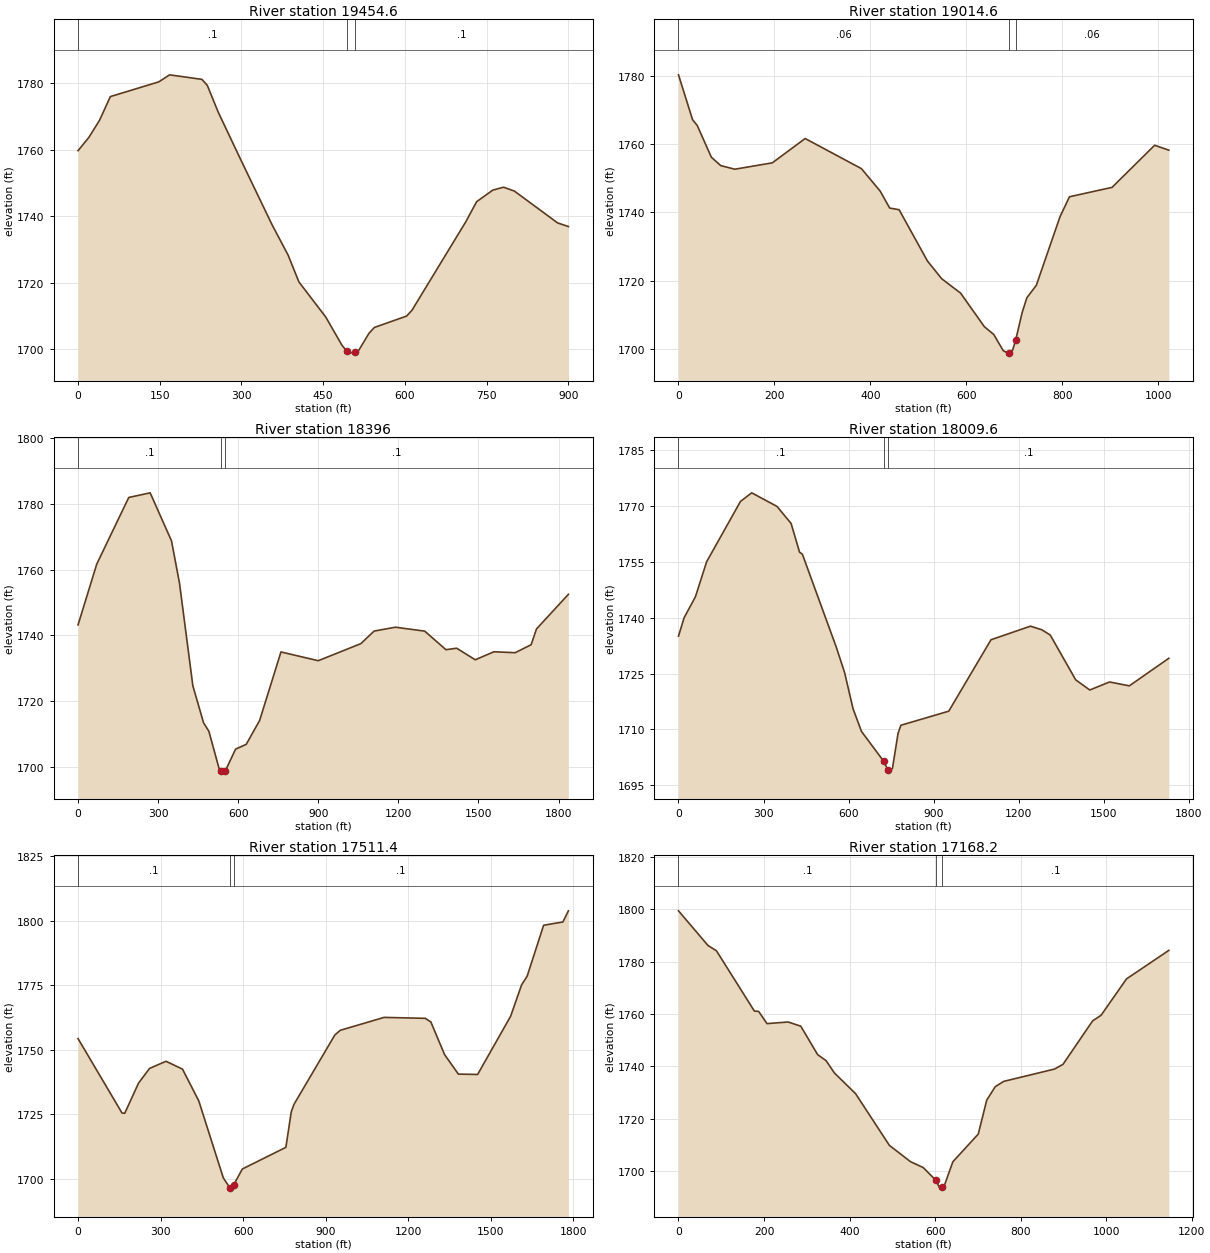
Type RM Length L Ch R = 1 ,19454.6 ,418.4,440,461.7
XS GIS Cut Line= 3
     1859488.189      300809.045     1860058.303      301343.323
      1860052.24      301462.284
#Sta/Elev= 30
       0  1759.7    19.8 1763.67    39.6 1768.88    59.3 1775.96   148.4  1780.4
   168.1 1782.51   227.5 1781.14   237.4 1779.32   257.2 1771.35   296.7 1757.68
     356 1737.49   385.7 1728.28   405.5 1720.22     455 1709.61   484.6 1701.16
     493 1699.47   504.4 1698.79     508 1698.99   514.3 1699.33   534.1 1704.73
     544  1706.5   603.3 1709.94   613.2  1711.7   712.1 1738.33   731.9 1744.35
   761.6 1747.83   781.3  1748.7   801.2 1747.54   880.6 1737.96   900.4 1736.87
#Mann= 3 , 0 , 0
       0      .1       0     493    .045       0     508      .1       0
Bank Sta=493,508
XS Rating Curve= 0 ,0
Exp/Cntr=0.3,0.1

Type RM Length L Ch R = 1 ,19014.6 ,633.7,618.6,605.1
XS GIS Cut Line= 3
      1859400.19      300677.965     1859553.345      301069.668
     1859471.553      301665.884
#Sta/Elev= 30
       0 1780.25    29.3 1767.14    39.1 1765.43    68.5 1756.16      88  1753.7
   117.4 1752.64   195.6  1754.5   264.1 1761.62   381.5  1752.8   420.6 1746.22
   440.3 1741.28     460 1740.79   519.2 1725.76   548.8  1720.6   588.3 1716.38
   637.6  1706.6   657.4 1704.28   677.1 1699.56     687 1698.84   688.2 1698.95
   696.8 1699.76   703.2 1702.75   716.6 1710.74   726.4 1715.05   746.1 1718.68
   795.5 1738.75   815.2 1744.58     904 1747.33   992.8 1759.65  1022.4 1758.21
#Mann= 3 , 0 , 0
       0     .06       0   688.2    .045       0   703.2     .06       0
Bank Sta=688.2,703.2
XS Rating Curve= 0 ,0
Exp/Cntr=0.3,0.1

Type RM Length L Ch R = 1 ,18396   ,377.8,385.8,392.2
XS GIS Cut Line= 3
     1858676.871       300804.17     1859099.761      301471.664
     1859909.934      302134.786
#Sta/Elev= 30
       0 1743.22      70 1761.68     190 1781.93   270.1 1783.34   350.1 1768.74
   380.1 1755.87   430.1  1724.7   470.1  1713.5   490.1 1710.89   530.1 1699.06
   537.1 1698.86   540.1 1698.78   552.1 1698.89   590.1 1705.46   630.1 1706.92
   680.2 1714.16   760.2 1734.99   899.9 1732.33  1059.4 1737.51  1109.2 1741.33
    1189 1742.51  1298.7 1741.32  1378.5 1735.67  1418.4 1736.13  1488.2 1732.61
    1558 1735.05  1637.7 1734.76  1697.5 1737.19  1717.5 1741.97  1837.1 1752.51
#Mann= 3 , 0 , 0
       0      .1       0   537.1    .045       0   552.1      .1       0
Bank Sta=537.1,552.1
XS Rating Curve= 0 ,0
Exp/Cntr=0.3,0.1

Type RM Length L Ch R = 1 ,18009.6 ,482.5,497.9,513.3
XS GIS Cut Line= 3
     1858619.448      300839.157     1858830.114      301972.077
     1859006.035      302522.645
#Sta/Elev= 30
       0 1735.07    19.9 1740.02    59.6 1745.61    99.3 1755.04   218.6 1771.23
   258.3 1773.55   347.7  1769.9   397.4 1765.31   427.2  1757.6   437.1 1757.07
   556.3 1732.21   586.1  1725.3   615.9 1715.57   645.7 1709.48   724.5 1701.42
   739.5 1699.05     745 1698.81     755 1699.56   774.8 1708.96   784.8 1711.13
   953.7 1714.91  1102.7 1734.09    1242 1737.74  1281.9 1736.78  1311.8 1735.36
  1401.5 1723.34  1451.3  1720.6  1521.1 1722.75  1590.8 1721.71  1730.3 1729.12
#Mann= 3 , 0 , 0
       0      .1       0   724.5    .045       0   739.5      .1       0
Bank Sta=724.5,739.5
XS Rating Curve= 0 ,0
Exp/Cntr=0.3,0.1

Type RM Length L Ch R = 1 ,17511.4 ,350.2,343,335.9
XS GIS Cut Line= 4
     1858482.068      300827.456     1858465.241      301206.496
     1858164.612      301763.086     1858185.071      302532.418
#Sta/Elev= 30
       0 1754.37   159.8 1725.56   169.7 1725.48   219.7 1737.13   259.6 1742.82
   319.5  1745.6   379.4 1742.57   438.7 1730.25   527.7 1700.48   550.8 1696.72
   557.3 1696.11   565.8 1697.82   596.9  1703.9     755 1712.28   774.8 1726.08
   784.7 1728.96   932.9 1755.76   952.7 1757.59    1112 1762.59  1261.9 1762.22
  1281.9  1760.8  1331.8 1748.17  1381.8 1740.63  1451.8  1740.5  1571.7 1763.04
  1611.7 1775.22  1631.7 1778.53  1691.6 1798.26  1761.6 1799.53  1781.6 1803.84
#Mann= 3 , 0 , 0
       0      .1       0   550.8    .045       0   565.8      .1       0
Bank Sta=550.8,565.8
XS Rating Curve= 0 ,0
Exp/Cntr=0.3,0.1

Type RM Length L Ch R = 1 ,17168.2 ,211,222.6,234.3
XS GIS Cut Line= 3
     1858280.313      300789.933     1858077.563      301206.496
     1857943.526      301876.446
#Sta/Elev= 30
       0 1799.45      69  1786.2    88.7 1784.19   177.4 1761.13   187.3 1761.01
     207 1756.34   256.3 1756.96   285.9 1755.36   325.3 1744.49     345  1742.2
   364.7 1737.45     414 1729.58     493 1709.82   542.5 1703.57   572.2 1701.32
   602.1  1696.4   611.8 1693.08   617.1 1693.83   621.7 1694.48   641.5 1703.54
   700.9 1714.12   720.7 1727.09   740.5 1732.22   760.3 1734.26   879.2 1738.97
     899 1740.77   968.3 1757.39   988.1 1759.54  1047.5 1773.43  1146.5 1784.34
#Mann= 3 , 0 , 0
       0      .1       0   602.1    .045       0   617.1      .1       0
Bank Sta=602.1,617.1
XS Rating Curve= 0 ,0
Exp/Cntr=0.3,0.1

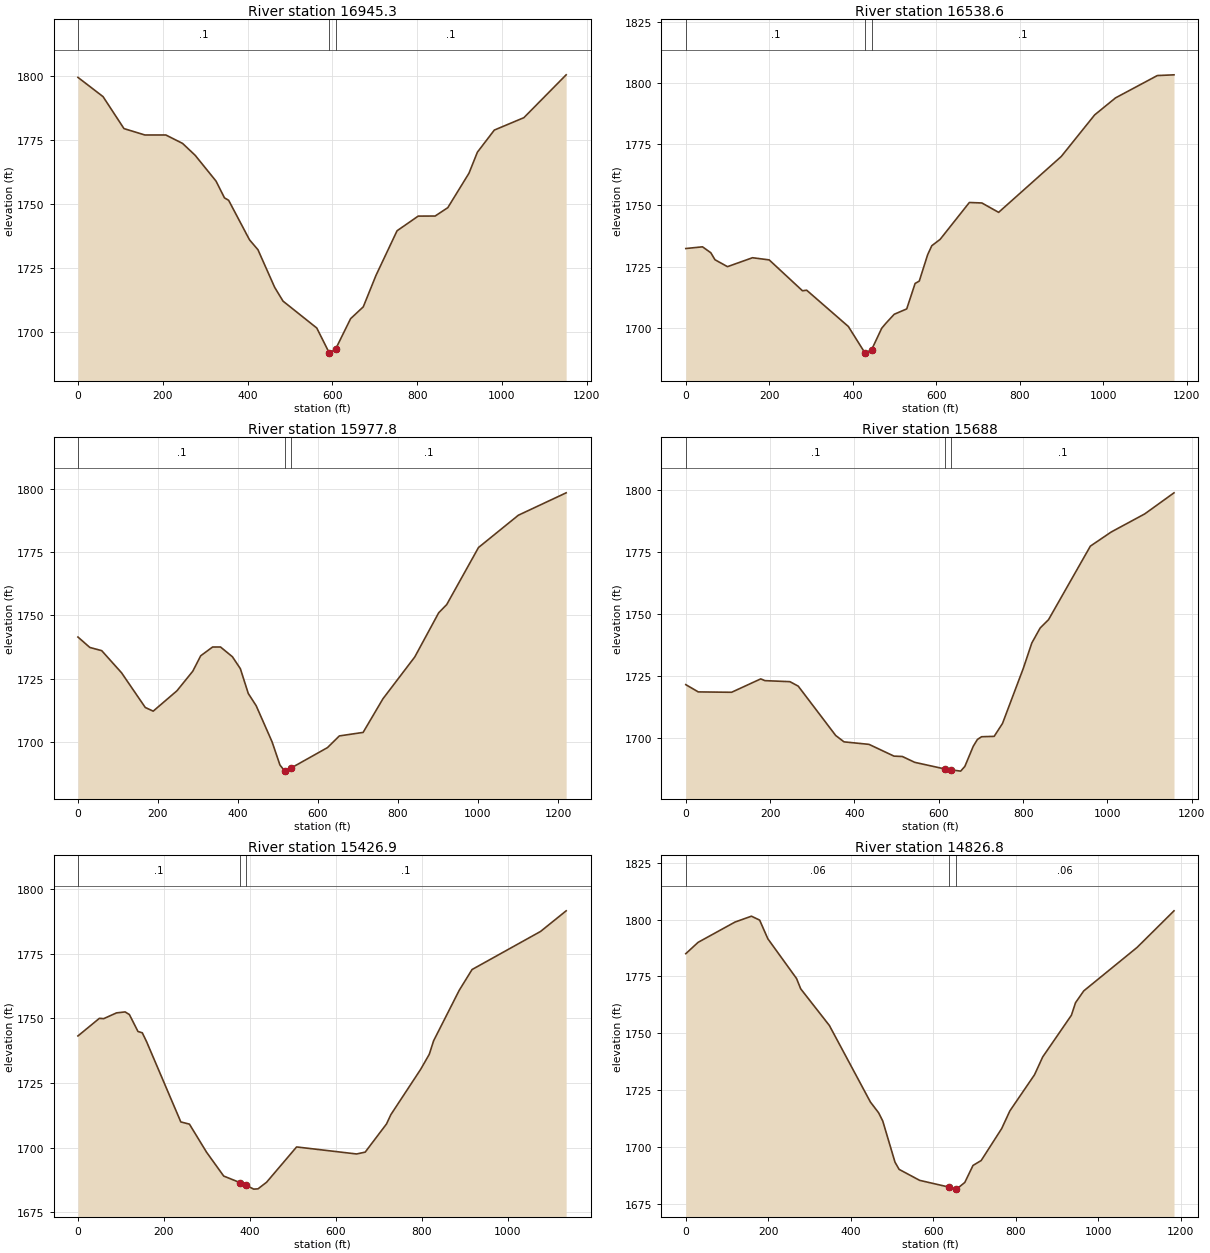
Type RM Length L Ch R = 1 ,16945.3 ,413.6,406.7,399.7
XS GIS Cut Line= 3
     1858208.923      300750.759     1857930.963       301170.66
     1857498.636       301653.52
#Sta/Elev= 30
       0 1799.65    59.2 1792.11   108.6 1779.58     158 1777.08   207.4 1777.08
   246.8 1773.78   276.5 1769.13   325.8    1759   345.6 1752.46   355.5 1751.49
   404.8 1735.99   424.6 1732.14   464.1 1717.38   483.8 1711.99   563.4 1701.46
   592.6 1691.78   593.3 1691.62   607.6 1693.13   643.2 1705.12   673.1 1709.76
     703 1722.05   752.8 1739.56   802.7  1745.3   842.6 1745.33   872.5 1748.61
   922.4 1762.09   942.3 1770.34   982.2    1779    1052 1783.87  1151.7 1800.65
#Mann= 3 , 0 , 0
       0      .1       0   592.6    .045       0   607.6      .1       0
Bank Sta=592.6,607.6
XS Rating Curve= 0 ,0
Exp/Cntr=0.3,0.1

Type RM Length L Ch R = 1 ,16538.6 ,587,560.7,534.4
XS GIS Cut Line= 3
     1857754.148      300582.084     1857546.511      301069.003
     1857347.779      301677.782
#Sta/Elev= 30
       0 1732.37      40 1733.07    59.9 1730.65    69.9 1727.78    99.9 1724.95
   159.8  1728.6   199.8 1727.72   279.6 1715.07   289.6 1715.31   389.5 1700.45
   429.5 1689.55   430.2 1689.55   445.2 1690.94   469.4 1699.74   479.4 1701.77
   499.4 1705.46   529.3 1707.65   549.4 1718.07   559.4 1719.05   579.4 1729.82
   589.4 1733.52   609.4 1736.13   679.4 1751.22   709.4 1751.02   749.5 1747.18
   899.6 1770.06   979.6 1787.08  1029.6 1794.04  1129.7 1803.18  1169.7 1803.48
#Mann= 3 , 0 , 0
       0      .1       0   430.2    .045       0   445.2      .1       0
Bank Sta=430.2,445.2
XS Rating Curve= 0 ,0
Exp/Cntr=0.3,0.1

Type RM Length L Ch R = 1 ,15977.8 ,283.2,289.8,293.2
XS GIS Cut Line= 3
     1856709.374      300595.433     1857227.279       301141.34
     1857275.684       301606.86
#Sta/Elev= 30
       0 1741.46    29.7 1737.35    59.4 1736.09   108.9 1727.38   168.3 1713.69
   188.1 1712.24   247.5 1720.27   287.1 1727.99   306.9 1734.07   336.6 1737.52
   356.4 1737.53   386.2 1733.68     406 1728.99   425.8 1719.21   445.6 1714.37
   485.2 1700.19     505 1691.01   517.1 1688.61   524.8  1688.6   532.1 1689.76
   623.8 1697.87   653.5 1702.48   712.9 1703.86   762.4  1717.1   842.1 1733.62
   901.9 1751.03   921.8 1754.23  1001.4 1776.75    1101 1789.47  1220.5  1798.3
#Mann= 3 , 0 , 0
       0      .1       0   517.1    .045       0   532.1      .1       0
Bank Sta=517.1,532.1
XS Rating Curve= 0 ,0
Exp/Cntr=0.3,0.1

Type RM Length L Ch R = 1 ,15688   ,254.1,260.4,269.9
XS GIS Cut Line= 3
     1856627.106      300649.381     1856907.022      301205.124
      1857210.76      301646.488
#Sta/Elev= 30
       0 1721.51    29.6 1718.59   108.6 1718.44   177.8 1723.83   187.7 1723.12
   246.9 1722.71   266.7 1720.91   355.6 1701.04   375.3 1698.49   434.6 1697.48
   493.8 1692.75   513.6  1692.6   543.2 1690.24   614.8 1687.57   629.8 1687.22
     652 1686.71   661.9  1688.6   681.8  1696.7   691.7 1699.46   701.6 1700.55
   731.4  1700.7   751.2 1705.89   800.8 1728.19   820.7 1738.26   840.5  1744.3
   860.4 1747.66   959.6 1777.25  1009.2 1782.95  1088.6 1790.22    1158  1798.7
#Mann= 3 , 0 , 0
       0      .1       0   614.8    .045       0   629.8      .1       0
Bank Sta=614.8,629.8
XS Rating Curve= 0 ,0
Exp/Cntr=0.3,0.1

Type RM Length L Ch R = 1 ,15426.9 ,625.6,600.2,574.7
XS GIS Cut Line= 3
     1856624.587      300848.138     1856686.485      301473.635
     1857150.864      301678.414
#Sta/Elev= 30
       0 1743.21    49.9 1750.03    59.9  1749.9    89.8 1752.14   109.8 1752.51
   119.7 1751.49   139.7 1744.93   149.7 1744.43   159.6 1741.04   239.4 1709.91
   259.4 1709.07   299.3 1698.19   339.2 1688.96   376.8 1686.44   391.8 1685.34
   409.1  1683.9     419 1684.01     439 1686.57   508.8 1700.23   648.4 1697.51
   668.4 1698.22   718.1 1709.15   728.1 1712.72   797.7 1730.33   817.6 1736.12
   827.6 1741.32   887.3 1760.89   917.1 1768.92  1076.4 1783.65  1136.1 1791.65
#Mann= 3 , 0 , 0
       0      .1       0   376.8    .045       0   391.8      .1       0
Bank Sta=376.8,391.8
XS Rating Curve= 0 ,0
Exp/Cntr=0.3,0.1

Type RM Length L Ch R = 1 ,14826.8 ,300.6,315.4,330.3
XS GIS Cut Line= 2
     1855959.357      301478.676      1857098.34      301801.987
#Sta/Elev= 30
       0    1785    29.8 1789.98   119.4 1798.91   159.2 1801.48   179.1 1799.75
     199 1791.55   268.6 1774.08   278.6 1769.57   348.2 1753.44   447.7  1719.8
   467.6 1715.07   477.6 1711.48   507.4 1693.33   517.4 1690.18   567.1 1685.36
   639.2 1682.35   654.2 1681.61   656.7  1681.5   676.6 1684.43   696.5  1691.9
   716.4 1694.08   766.1 1708.13     786 1715.91   845.7 1731.77   865.6 1739.62
   935.2 1757.95   945.2 1763.46   965.1 1768.64  1094.4 1787.74    1184 1803.84
#Mann= 3 , 0 , 0
       0     .06       0   639.2    .045       0   654.2     .06       0
Bank Sta=639.2,654.2
XS Rating Curve= 0 ,0
Exp/Cntr=0.3,0.1

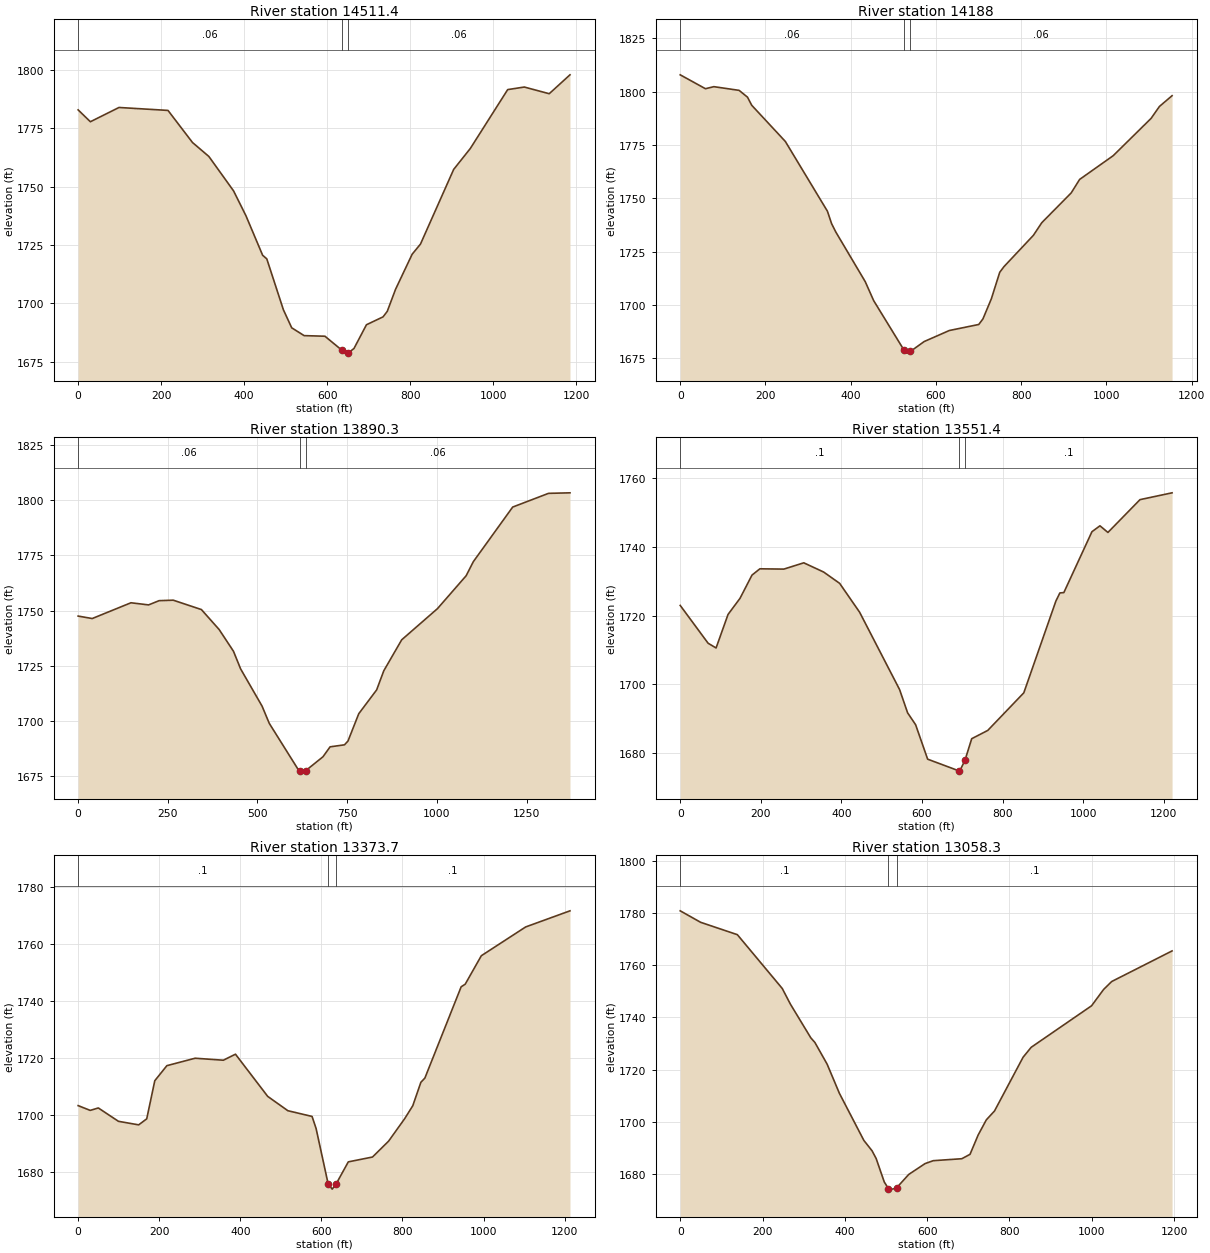
Type RM Length L Ch R = 1 ,14511.4 ,332,323.3,314.7
XS GIS Cut Line= 3
     1855915.692      301544.318     1856240.167      301659.329
      1856739.58      302334.982
#Sta/Elev= 30
       0 1782.86    29.5 1777.78    98.4 1783.89   216.4 1782.63   275.4 1768.89
   314.8 1762.92   374.3 1748.18   404.3 1737.46   444.3 1720.61   454.3 1719.08
   494.3 1697.27   514.3 1689.55   544.3  1686.2   594.3 1685.95   635.3 1679.94
   644.3 1678.71   650.3 1678.75   664.3 1680.71   694.3 1690.86   734.3 1694.24
   744.4 1696.59   764.4 1706.05   804.4 1721.07   824.4  1725.4   904.4 1757.39
   944.4 1766.33  1034.4 1791.54  1074.4 1792.64  1134.4 1789.78  1184.4 1797.87
#Mann= 3 , 0 , 0
       0     .06       0   635.3    .045       0   650.3     .06       0
Bank Sta=635.3,650.3
XS Rating Curve= 0 ,0
Exp/Cntr=0.3,0.1

Type RM Length L Ch R = 1 ,14188   ,304.9,297.6,290.2
XS GIS Cut Line= 3
     1855704.399      301786.949     1856157.376      302067.344
     1856684.343      302396.182
#Sta/Elev= 30
       0 1807.94    59.2 1801.43    78.9 1802.39   138.1 1800.66   157.8 1797.48
   167.7 1793.68   246.6 1776.72   345.3 1744.03   355.2 1738.16     365 1734.28
   434.1 1710.99   453.8 1702.13   525.2 1678.86   532.7 1677.51   540.2 1678.33
   572.2 1682.92   631.3 1688.11   700.4 1690.94   710.2 1693.55   729.9 1702.96
   749.6  1715.4   759.5 1718.04   828.5  1732.7   848.2 1738.63   917.3 1752.61
     937 1758.91  1015.9 1770.06  1104.6 1787.51  1124.3 1793.12  1153.9 1798.16
#Mann= 3 , 0 , 0
       0     .06       0   525.2    .045       0   540.2     .06       0
Bank Sta=525.2,540.2
XS Rating Curve= 0 ,0
Exp/Cntr=0.3,0.1

Type RM Length L Ch R = 1 ,13890.3 ,316.9,338.9,361
XS GIS Cut Line= 3
     1855583.827      302061.674     1855875.294      302294.599
     1856846.117      302525.903
#Sta/Elev= 30
       0 1747.53    39.3 1746.42   147.3 1753.55   196.4 1752.58   225.8  1754.5
   265.1 1754.72   343.6 1750.48   393.1 1741.45     433 1731.63   452.9 1723.67
   512.8  1706.8   532.8 1699.02   612.6 1678.36   619.7 1677.69   622.6 1677.41
   634.7 1677.66   682.5  1683.9   702.4  1688.4   742.4  1689.3   752.3 1691.03
   782.3 1703.37   832.2 1714.15   852.1  1722.8     902  1736.8  1001.8 1750.91
  1081.7 1765.78  1101.6 1772.12  1211.4 1796.83  1311.2 1803.03  1371.1 1803.27
#Mann= 3 , 0 , 0
       0     .06       0   619.7    .045       0   634.7     .06       0
Bank Sta=619.7,634.7
XS Rating Curve= 0 ,0
Exp/Cntr=0.3,0.1

Type RM Length L Ch R = 1 ,13551.4 ,172.5,177.7,182.9
XS GIS Cut Line= 3
     1855548.277      302128.556     1855914.387      302415.138
     1856184.703      303120.968
#Sta/Elev= 30
       0 1722.99    69.2    1712      89 1710.62   118.7 1720.37   148.4 1725.05
   178.1  1731.8   197.8 1733.64   257.2 1733.55   306.7 1735.38   356.1 1732.69
   395.7 1729.41   445.2 1721.03   544.5 1698.52   564.4 1691.76   584.3  1688.3
   614.1 1678.29   691.9 1674.88   693.7 1674.81   706.9 1678.02   723.5 1684.24
   763.3 1686.64   852.8 1697.58   932.4 1724.25   942.3 1726.62   952.2 1726.73
  1021.9 1744.42  1041.8 1746.14  1061.6 1744.21  1141.2 1753.75  1220.8 1755.73
#Mann= 3 , 0 , 0
       0      .1       0   691.9    .045       0   706.9      .1       0
Bank Sta=691.9,706.9
XS Rating Curve= 0 ,0
Exp/Cntr=0.3,0.1

Type RM Length L Ch R = 1 ,13373.7 ,331.8,315.3,298.6
XS GIS Cut Line= 3
     1855478.636      302160.432     1855787.333      302395.591
     1855898.098      303213.297
#Sta/Elev= 30
       0 1703.41    29.8 1701.74    49.8 1702.59    99.5 1697.91   149.3 1696.67
   169.2 1698.78   189.1 1712.14   218.9 1717.41   288.6 1720.02   358.2 1719.32
   388.1 1721.43   467.6 1706.65   517.3 1701.63     577 1699.62   586.9 1695.43
   616.7 1675.99   626.7 1674.15   636.6 1676.02   666.4  1683.7   726.1  1685.4
   765.8 1690.96   805.6 1698.87   825.5 1703.39   845.4 1711.58   855.3 1713.07
   944.8 1745.05   954.8 1745.97   994.5 1755.93  1103.9 1766.02  1213.2 1771.67
#Mann= 3 , 0 , 0
       0      .1       0   616.7    .045       0   636.6      .1       0
Bank Sta=616.7,636.6
XS Rating Curve= 0 ,0
Exp/Cntr=0.3,0.1

Type RM Length L Ch R = 1 ,13058.3 ,333,348.6,364.3
XS GIS Cut Line= 3
     1855111.737      302349.942     1855738.467       302913.58
     1855885.876      303233.336
#Sta/Elev= 30
       0 1780.91    49.6  1776.5   138.8 1771.76   247.9  1751.1   267.7 1745.09
   317.3 1732.15   327.2 1730.38     357 1722.03   386.7 1710.87   446.2 1692.77
   466.1  1688.8     476 1685.84   495.8 1676.81   505.7 1674.31   515.7 1674.08
   525.6 1674.56   555.3 1679.73     595 1683.89   614.8    1685   684.2 1685.75
   704.1 1687.44   723.9 1694.86   743.7 1700.67   763.6 1704.08     833  1724.7
   852.7 1728.52   999.4 1744.46  1028.7 1750.73  1048.3 1753.77    1195 1765.52
#Mann= 3 , 0 , 0
       0      .1       0   505.7    .045       0   525.6      .1       0
Bank Sta=505.7,525.6
XS Rating Curve= 0 ,0
Exp/Cntr=0.3,0.1