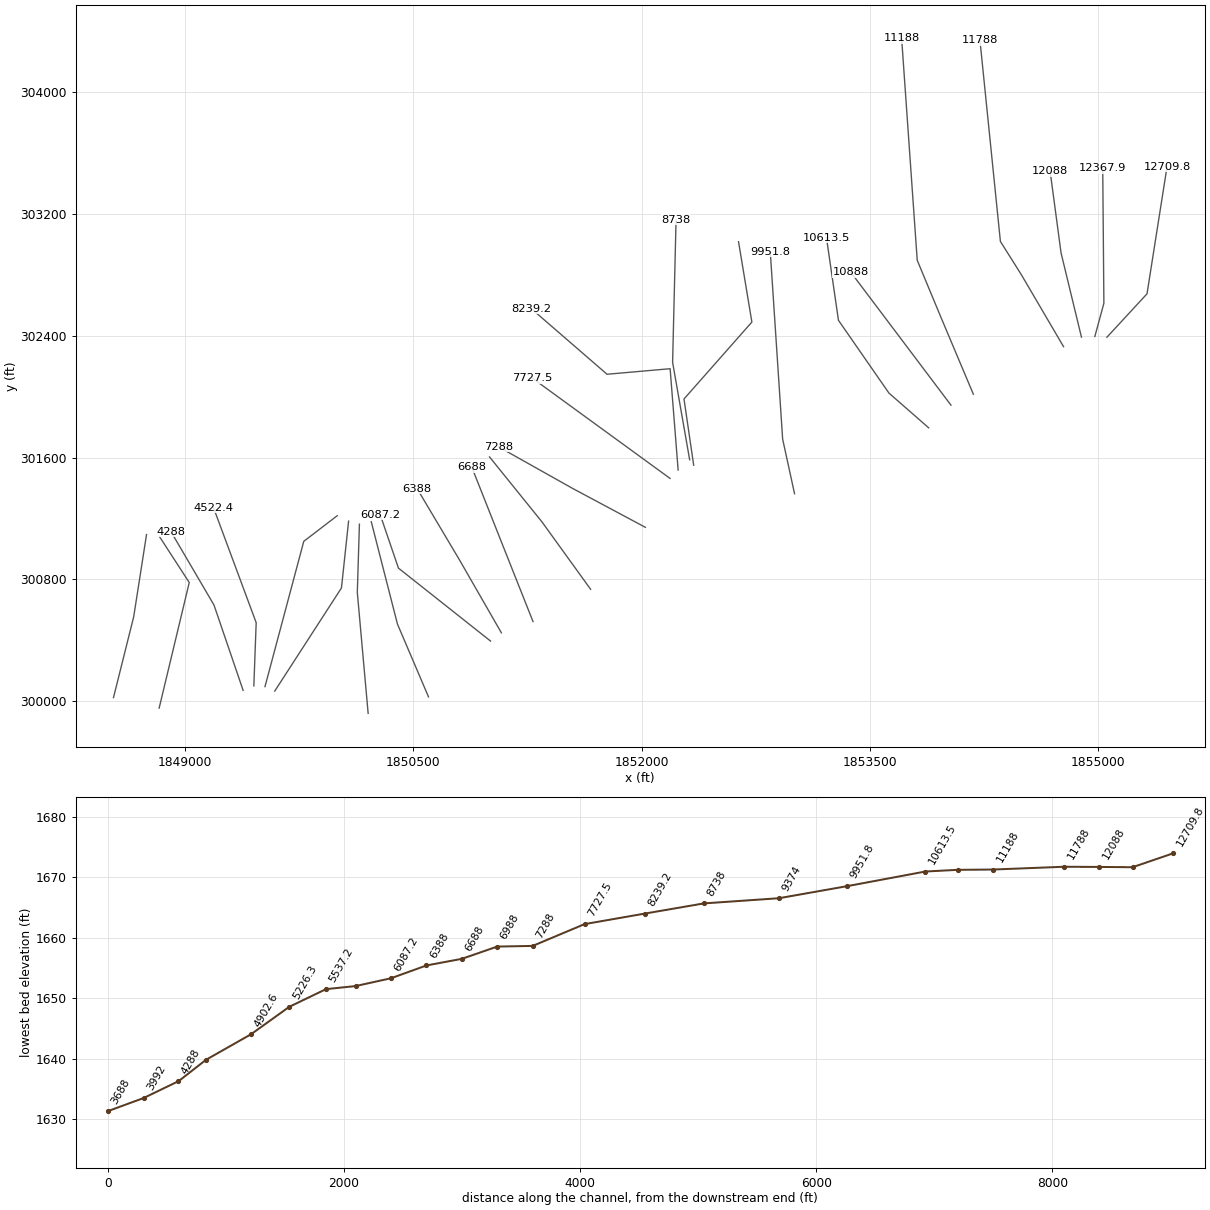
HEC-RAS study SndlckCrk.prj: SndlckCrk

--- SndlckCrk.g01 (geometry) --- (continued)

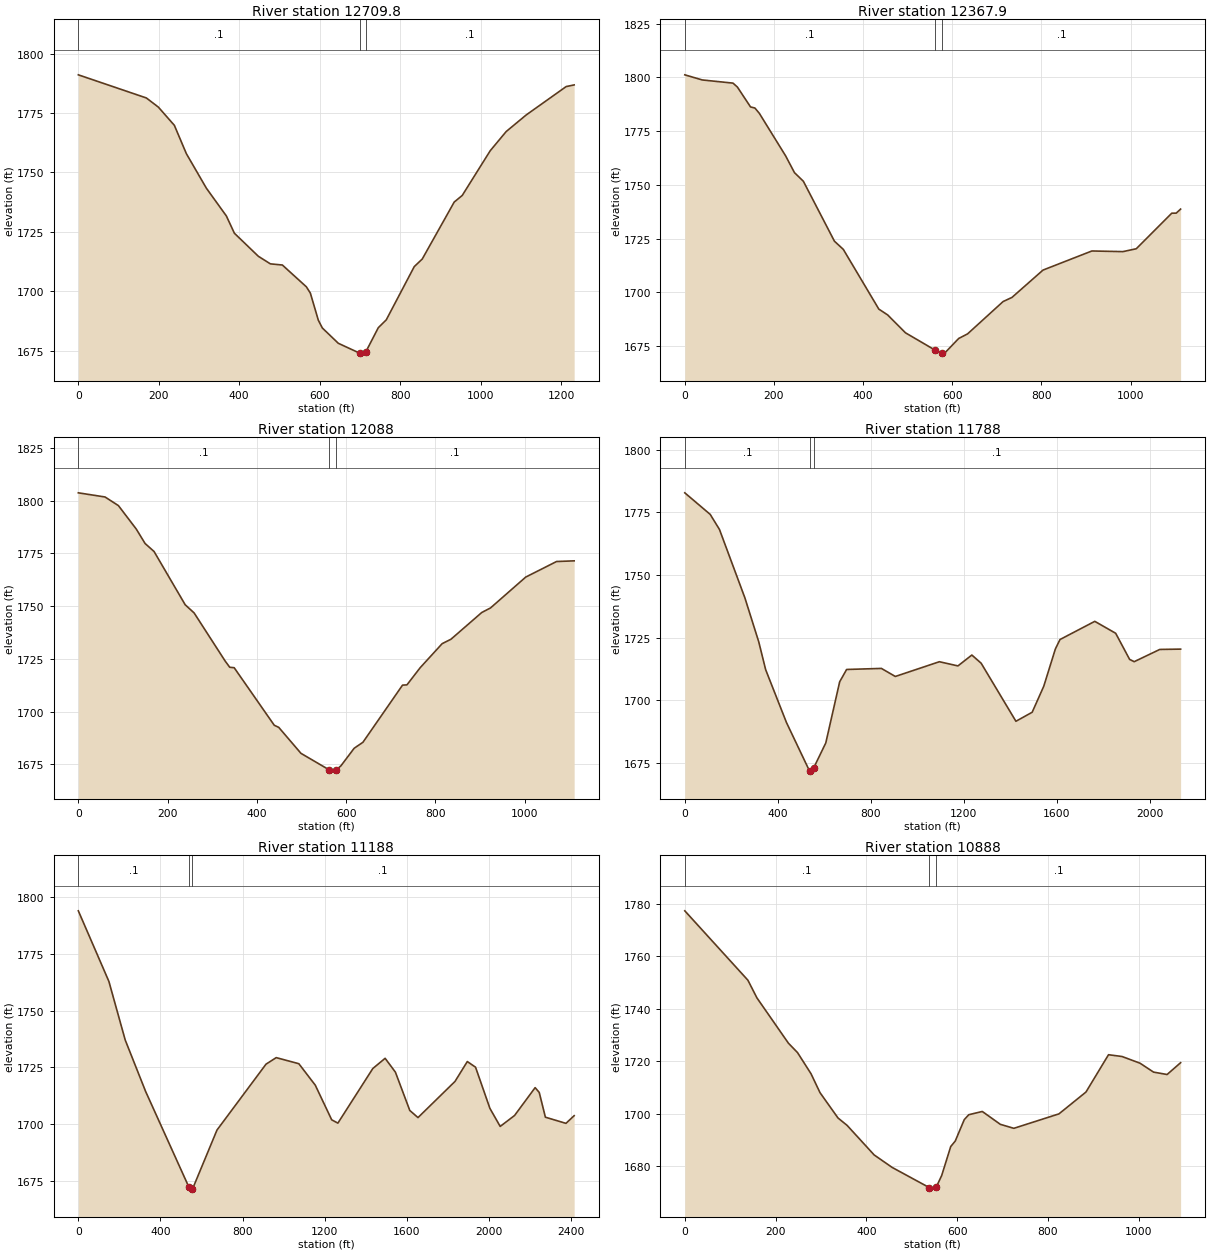
Type RM Length L Ch R = 1 ,12709.8 ,338.2,341.9,345.5
XS GIS Cut Line= 3
     1855058.076      302390.797     1855321.469      302675.761
     1855453.037      303510.157
#Sta/Elev= 30
       0  1791.1   169.2 1781.36     199 1777.51   238.8 1769.84   268.6 1757.92
   318.4 1743.38   368.2 1731.67     388 1724.44   447.7 1714.72   477.5 1711.55
   507.3 1711.06   566.9  1701.9   576.9 1699.24   596.7 1687.85   606.7 1684.56
   646.4 1678.12   699.2 1673.99     706 1673.98   714.2 1674.32   745.8 1684.67
   765.7    1688   835.2 1710.38   855.1 1713.58   934.6 1737.56   954.5 1740.33
  1024.1 1759.15  1063.8 1767.23  1113.5  1774.2  1212.9 1786.15  1232.8 1786.86
#Mann= 3 , 0 , 0
       0      .1       0   699.2    .045       0   714.2      .1       0
Bank Sta=699.2,714.2
XS Rating Curve= 0 ,0
Exp/Cntr=0.3,0.1

Type RM Length L Ch R = 1 ,12367.9 ,274.8,279.9,282.7
XS GIS Cut Line= 3
     1854978.699      302395.635     1855038.041      302613.863
     1855030.458      303500.116
#Sta/Elev= 30
       0 1801.16    39.3 1798.77   108.2  1797.3     118 1795.47   147.5 1786.22
   157.3 1785.71   167.2 1783.26   226.2 1763.46   246.1 1755.64     266 1751.65
   335.7 1723.77   355.6 1719.96   435.3 1692.17   455.2 1689.45     495 1681.16
   561.9 1673.04   574.7 1671.69   576.9 1671.77   584.6 1672.04   614.5 1678.51
   634.4 1680.64   714.1 1695.68     734  1697.6   803.7 1710.33   913.3 1719.21
     983 1718.91  1012.9 1720.25  1092.5 1736.78  1102.5 1736.82  1112.4  1738.7
#Mann= 3 , 0 , 0
       0      .1       0   561.9    .045       0   576.9      .1       0
Bank Sta=561.9,576.9
XS Rating Curve= 0 ,0
Exp/Cntr=0.3,0.1

Type RM Length L Ch R = 1 ,12088   ,293.3,300,309.7
XS GIS Cut Line= 3
     1854890.628      302391.175     1854756.661      302943.717
     1854684.679      303480.937
#Sta/Elev= 30
       0 1803.69    59.8 1801.72    89.8 1797.63   129.7 1786.53   149.6 1779.64
   169.6 1775.88   239.4 1750.61   259.3 1746.76   329.2 1723.83   339.1 1720.99
   349.1 1720.77   438.9 1693.48   448.9 1692.49   498.7 1680.17   561.1 1672.44
   568.6 1671.74   576.1 1672.05   588.3 1674.28   617.8 1682.57   637.5 1685.42
   726.2 1712.52   736.1 1712.64   765.6 1720.75   814.9 1732.17   834.6 1734.26
   903.6 1746.94   923.3 1749.12  1002.2 1763.75  1071.2 1771.12  1110.6 1771.44
#Mann= 3 , 0 , 0
       0      .1       0   561.1    .045       0   576.1      .1       0
Bank Sta=561.1,576.1
XS Rating Curve= 0 ,0
Exp/Cntr=0.3,0.1

Type RM Length L Ch R = 1 ,11788   ,602.9,599.9,596.1
XS GIS Cut Line= 4
     1854773.011      302328.547     1854496.162      302800.337
     1854357.995      303019.559     1854223.592      304340.494
#Sta/Elev= 30
       0 1782.81   109.4  1774.2   149.2  1768.2   258.6 1740.91   318.3 1723.35
   348.1 1712.22   437.6 1691.15   537.1 1671.77   539.5 1671.78   554.5 1673.02
   606.8 1683.02   666.6 1707.42   696.5 1712.33   846.1 1712.75     906 1709.54
  1095.7 1715.42  1175.5 1713.75  1235.4 1718.09  1275.4 1714.83  1425.1 1691.66
    1495 1695.26  1544.9 1705.64  1594.8  1720.5  1614.8 1724.28  1764.5 1731.53
  1854.4 1726.77  1914.3 1716.36  1934.2 1715.44  2044.1 1720.32  2133.9 1720.45
#Mann= 3 , 0 , 0
       0      .1       0   539.5    .045       0   554.5      .1       0
Bank Sta=539.5,554.5
XS Rating Curve= 0 ,0
Exp/Cntr=0.3,0.1

Type RM Length L Ch R = 1 ,11188   ,294.4,300,305.7
XS GIS Cut Line= 4
     1854180.202      302016.302      1853968.07      302519.406
     1853811.362      302896.018      1853708.86      304353.526
#Sta/Elev= 30
       0 1794.06   148.9 1762.92   228.3  1737.1   327.6 1714.43   538.5  1672.2
   553.5  1671.5     556 1671.31   675.3 1697.36   914.1 1726.42   963.9 1729.31
    1074 1726.63  1154.1 1717.16  1234.1 1701.88  1264.2 1700.42  1434.3  1724.5
  1494.3 1729.01  1544.4  1722.9  1614.4 1706.01  1654.4 1702.86  1834.6 1718.81
  1894.6 1727.58  1934.7 1725.09  2004.7 1706.92  2054.8 1698.96  2124.8 1703.79
  2224.9 1716.07  2244.9 1713.96  2274.9 1703.04    2375 1700.32    2415  1703.7
#Mann= 3 , 0 , 0
       0      .1       0   538.5    .045       0   553.5      .1       0
Bank Sta=538.5,553.5
XS Rating Curve= 0 ,0
Exp/Cntr=0.3,0.1

Type RM Length L Ch R = 1 ,10888   ,275.4,274.5,273.5
XS GIS Cut Line= 3
     1854033.159      301944.479     1853704.432      302380.432
     1853375.705      302816.384
#Sta/Elev= 30
       0 1777.34     139 1750.89   158.8 1744.17   228.3 1726.87   248.2 1723.32
     278 1715.24   297.8 1708.03   337.5 1698.36   357.4 1695.57     417  1684.3
   456.6 1679.54   538.5 1671.84     546 1671.26   553.5 1671.92   565.8 1676.46
   585.7  1687.5   595.6 1689.57   615.5 1697.75   625.4 1699.62   655.2 1700.86
   694.9 1695.96   724.7 1694.44     824 1699.94   883.5 1708.26   933.2 1722.49
     963 1721.81  1002.6 1719.26  1032.4 1715.86  1062.2 1714.95    1092 1719.45
#Mann= 3 , 0 , 0
       0      .1       0   538.5    .045       0   553.5      .1       0
Bank Sta=538.5,553.5
XS Rating Curve= 0 ,0
Exp/Cntr=0.3,0.1

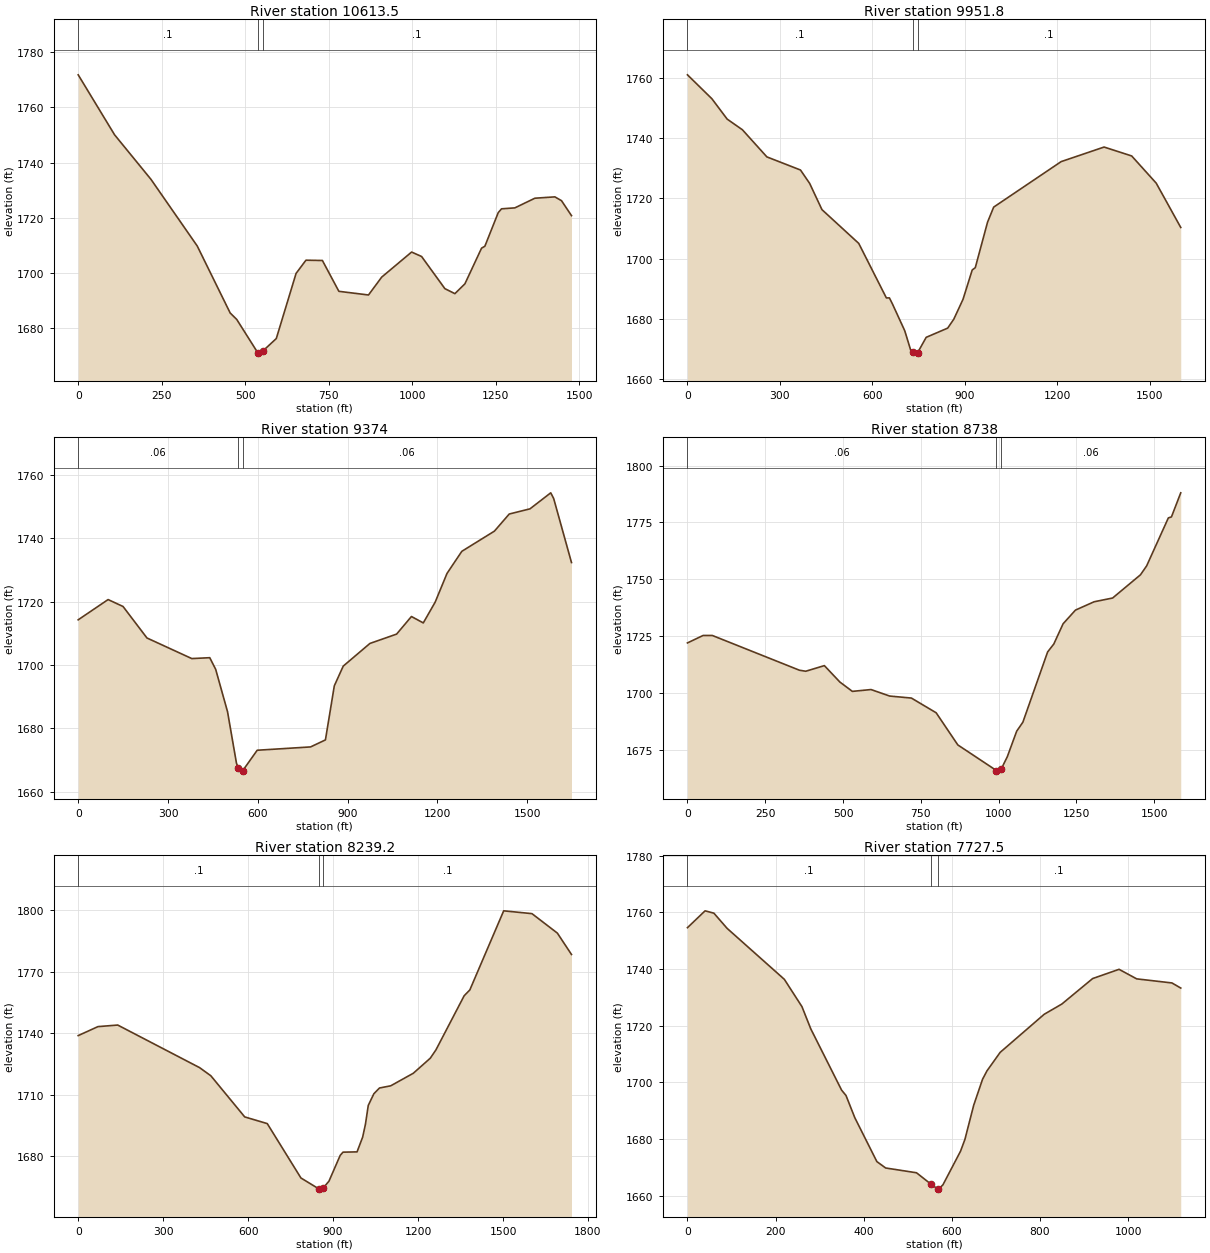
Type RM Length L Ch R = 1 ,10613.5 ,673.8,661.7,649.6
XS GIS Cut Line= 4
     1853886.513      301795.679     1853625.543      302023.803
     1853293.687      302501.787     1853214.907      303044.843
#Sta/Elev= 30
       0 1771.84   108.9 1750.11   217.9 1733.96   356.5  1709.8   455.1 1685.53
   474.8 1683.18   537.7 1671.13   543.9 1670.98   552.7 1671.73   593.2 1676.26
   652.4 1699.86     682 1704.66   731.3 1704.55   780.6 1693.38   869.3 1692.05
   908.8 1698.52   998.4 1707.61  1028.3    1706  1098.1 1694.34    1128 1692.53
    1158 1696.09  1207.9 1709.02  1217.8 1709.72  1257.8 1721.89  1267.7 1723.28
  1307.6 1723.62  1367.5 1727.12  1427.4 1727.61  1447.3 1726.23  1477.2 1720.81
#Mann= 3 , 0 , 0
       0      .1       0   537.7    .045       0   552.7      .1       0
Bank Sta=537.7,552.7
XS Rating Curve= 0 ,0
Exp/Cntr=0.3,0.1

Type RM Length L Ch R = 1 ,9951.8  ,596.2,577.7,559.3
XS GIS Cut Line= 3
     1853005.176       301362.87     1852926.989      301721.227
     1852845.544      302952.674
#Sta/Elev= 30
       0 1761.04    79.3 1753.09   128.9 1746.32   178.4 1742.78   257.7 1733.77
   366.8 1729.41   396.6 1724.96   436.5 1716.24   555.9 1705.02   645.5 1686.91
   655.4 1686.91   665.4 1684.87   705.2 1675.99   725.1 1669.34     732 1668.82
     745 1668.56     747 1668.72   774.8 1673.81   844.5 1676.87   864.4 1679.84
   894.3 1686.45   924.1 1696.18   934.1 1696.96   973.9 1712.08   993.8 1717.08
  1212.8  1732.2  1352.1 1737.04  1441.7 1734.08  1521.3 1725.04  1600.9 1710.32
#Mann= 3 , 0 , 0
       0      .1       0     732    .045       0     747      .1       0
Bank Sta=732,747
XS Rating Curve= 0 ,0
Exp/Cntr=0.3,0.1

Type RM Length L Ch R = 1 ,9374    ,620.5,636,651.6
XS GIS Cut Line= 4
     1852342.331      301550.171     1852278.688      301985.109
     1852724.742        302490.3     1852637.046       303017.83
#Sta/Elev= 30
       0 1714.25    99.9 1720.63   149.8 1718.45   229.8 1708.52   379.6 1702.03
   439.6 1702.31   459.4 1698.63     499 1685.28   528.8 1669.08     535  1667.5
   538.7 1666.56     550 1666.74   598.1 1673.14   776.5 1674.19   826.1  1676.4
   855.8 1693.45   885.6 1699.66   974.8  1706.8    1064 1709.75  1113.5 1715.29
  1153.1 1713.27  1192.7  1719.8  1232.3 1728.86  1281.8 1735.83  1390.8  1742.2
  1440.3 1747.59  1509.6 1749.22    1579 1754.27  1588.8 1752.47  1648.3  1732.3
#Mann= 3 , 0 , 0
       0     .06       0     535    .045       0     550     .06       0
Bank Sta=535,550
XS Rating Curve= 0 ,0
Exp/Cntr=0.3,0.1

Type RM Length L Ch R = 1 ,8738    ,460.3,498.8,537.3
XS GIS Cut Line= 3
     1852315.827      301585.997     1852203.759      302226.185
     1852226.563      303161.173
#Sta/Elev= 30
       0 1722.06      50 1725.32      80 1725.33     360 1710.05     380 1709.61
     440 1712.08   489.9 1704.85   529.9 1700.76   589.9 1701.56   649.9  1698.7
   719.6 1697.82   799.2 1691.35   868.8 1677.22     993 1665.95   998.2  1665.7
    1008 1666.53    1028 1672.08  1057.9 1683.24  1077.8 1687.19  1157.4 1718.09
  1177.2 1721.56  1207.1 1730.47  1246.9 1736.49  1306.6 1740.14  1366.3  1741.8
  1455.8 1752.01  1475.7 1755.95  1545.4 1777.02  1555.3 1777.45  1585.2 1788.04
#Mann= 3 , 0 , 0
       0     .06       0     993    .045       0    1008     .06       0
Bank Sta=993,1008
XS Rating Curve= 0 ,0
Exp/Cntr=0.3,0.1

Type RM Length L Ch R = 1 ,8239.2  ,528.2,511.7,495.2
XS GIS Cut Line= 4
     1852240.142      301518.323      1852187.47      302183.834
      1851773.05      302147.438     1851275.287      302578.027
#Sta/Elev= 30
       0 1738.87    69.8 1743.24   139.5 1744.01   428.4 1723.26   468.3 1719.29
   587.9 1699.23   667.6 1695.96   786.4 1669.46   850.2  1664.1   855.8 1664.02
   865.2 1664.61   885.5 1667.91   925.1 1680.48     935 1682.04   984.6 1682.18
  1004.4 1689.37  1014.3 1695.69  1024.2 1704.82    1044 1710.52  1063.8 1713.32
  1103.6 1714.39  1183.3 1720.51  1243.2 1727.84  1263.1 1731.88  1362.8 1758.28
  1382.8 1761.11  1502.4 1799.69  1602.2 1798.32  1691.9 1788.83  1741.8 1778.41
#Mann= 3 , 0 , 0
       0      .1       0   850.2    .045       0   865.2      .1       0
Bank Sta=850.2,865.2
XS Rating Curve= 0 ,0
Exp/Cntr=0.3,0.1

Type RM Length L Ch R = 1 ,7727.5  ,436.5,439.6,442.2
XS GIS Cut Line= 2
     1852186.986      301463.443     1851281.803      302121.936
#Sta/Elev= 30
       0 1754.61      40 1760.56      60 1759.73      90 1754.36   219.9 1736.36
   259.8 1726.72   279.8 1718.89   349.8 1697.23   359.8 1695.33   379.8 1687.48
   429.8    1672   449.7 1669.74   519.7 1668.05   552.6 1664.03   567.6 1662.33
   569.7 1662.27   579.7 1663.78   619.6 1675.64   629.6 1679.82   649.6 1691.92
   669.6 1701.06   679.6 1704.02   709.6 1710.57   809.5 1724.02   849.5 1727.63
   919.5 1736.64   979.4  1739.9  1019.4 1736.53  1099.4 1735.09  1119.4 1733.29
#Mann= 3 , 0 , 0
       0      .1       0   552.6    .045       0   567.6      .1       0
Bank Sta=552.6,567.6
XS Rating Curve= 0 ,0
Exp/Cntr=0.3,0.1

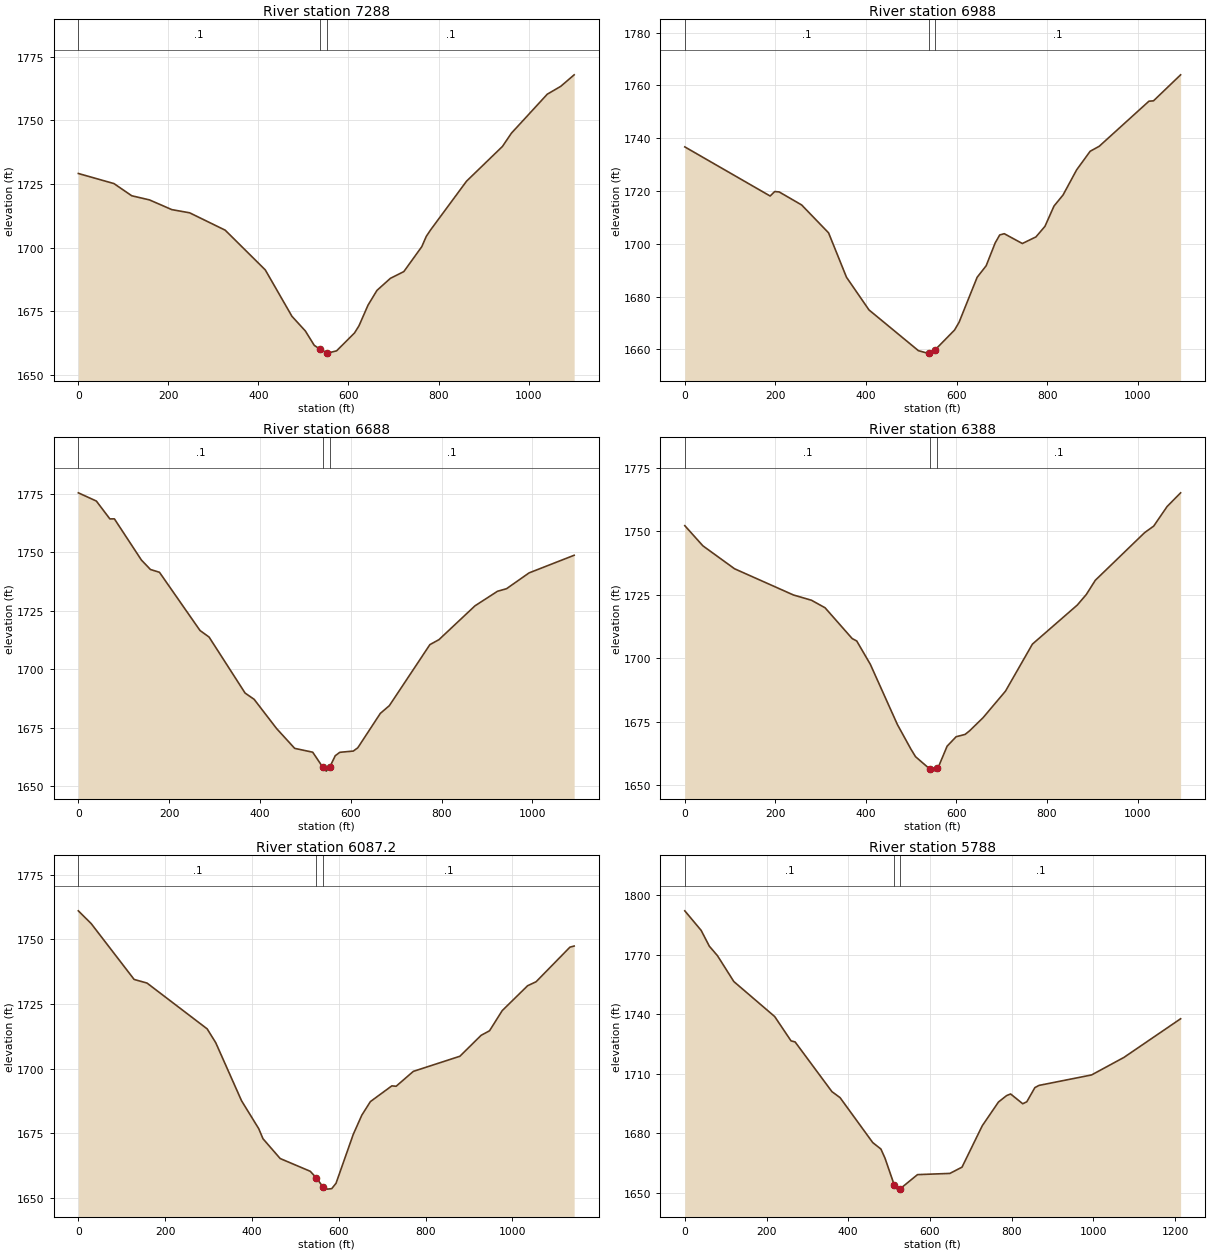
Type RM Length L Ch R = 1 ,7288    ,310.1,299.9,291.3
XS GIS Cut Line= 3
     1852024.674      301142.223     1851545.144      301398.537
     1851059.012      301671.432
#Sta/Elev= 30
       0 1729.15    79.1 1725.19   118.6 1720.41   158.2 1718.77   207.6 1714.97
   247.2 1713.72   326.2  1706.9   415.2 1691.32   474.5 1673.09   504.2 1667.36
     524 1661.71   536.2 1660.28   551.2 1658.85   553.7 1658.66   573.6 1659.56
   613.4 1666.58   623.4 1669.41   643.3 1677.45   663.2 1683.27   693.1 1688.01
   722.9 1690.65   762.8 1700.43   772.7 1704.45   782.7 1707.09   862.3 1726.15
   941.9 1739.75   961.8 1744.95  1041.5 1760.26  1071.4 1763.34  1101.2 1767.86
#Mann= 3 , 0 , 0
       0      .1       0   536.2    .045       0   551.2      .1       0
Bank Sta=536.2,551.2
XS Rating Curve= 0 ,0
Exp/Cntr=0.3,0.1

Type RM Length L Ch R = 1 ,6988    ,305.6,300,293.2
XS GIS Cut Line= 3
     1851665.009      300735.237      1851345.64      301177.433
     1851000.625      301604.506
#Sta/Elev= 30
       0 1736.71   188.4 1718.09   198.4 1719.78   208.3 1719.64   257.9 1714.71
   317.4 1704.13     357 1687.28   406.6 1674.92   515.7 1659.48   535.6 1658.55
     538 1658.61     553 1659.87   595.4 1667.29   605.4 1670.23   645.3 1687.28
   665.2 1691.65   685.2 1700.34   695.2 1703.34   705.2 1703.81   745.1 1700.09
   775.1 1702.59     795 1706.59     815 1714.29     835 1718.49   864.9 1727.99
   894.8 1735.05   914.8 1736.94  1024.6 1754.03  1034.6 1754.16  1094.5 1764.02
#Mann= 3 , 0 , 0
       0      .1       0     538    .045       0     553      .1       0
Bank Sta=538,553
XS Rating Curve= 0 ,0
Exp/Cntr=0.3,0.1

Type RM Length L Ch R = 1 ,6688    ,296.7,300,303.6
XS GIS Cut Line= 3
     1851286.445      300523.379      1851084.87      301030.807
     1850883.685      301538.391
#Sta/Elev= 30
       0 1775.35    39.7 1771.84    69.5 1764.21    79.4 1764.24     139 1746.63
   158.8 1742.62   178.7 1741.42     268 1716.56   287.9 1713.78   367.3 1689.85
   387.2 1687.18   436.8 1674.66   476.5 1666.24   516.2  1664.6   538.5 1658.17
     546 1656.52   553.5 1658.15   565.8 1663.09   575.8 1664.55   605.6 1665.09
   615.5 1666.49   665.1 1681.17     685 1684.48   774.3 1710.54   794.2 1712.65
   873.6  1727.1   923.2 1733.32   943.1 1734.41   992.7 1741.16    1092 1748.69
#Mann= 3 , 0 , 0
       0      .1       0   538.5    .045       0   553.5      .1       0
Bank Sta=538.5,553.5
XS Rating Curve= 0 ,0
Exp/Cntr=0.3,0.1

Type RM Length L Ch R = 1 ,6388    ,292.2,300.8,309
XS GIS Cut Line= 3
     1851078.569      300449.372     1850804.662      300925.852
     1850525.804      301394.526
#Sta/Elev= 30
       0 1752.28      40 1744.32   109.9 1735.27   239.8 1724.94   279.8 1722.85
   309.8 1719.88   369.7 1707.72   379.7 1706.78   409.7 1697.58   469.7 1673.74
   499.6 1664.03   509.6 1661.11   542.1  1656.1   549.6 1655.42   557.1 1656.47
   559.5  1656.8   579.3 1665.26   599.2 1668.99     619 1669.91   628.9 1671.32
   658.7  1676.5   708.2 1686.98   767.7 1705.54   866.9 1720.97   886.7 1725.12
   906.6 1730.73  1015.6 1749.55  1035.5  1752.1  1065.2 1759.85    1095 1765.24
#Mann= 3 , 0 , 0
       0      .1       0   542.1    .045       0   557.1      .1       0
Bank Sta=542.1,557.1
XS Rating Curve= 0 ,0
Exp/Cntr=0.3,0.1

Type RM Length L Ch R = 1 ,6087.2  ,310.3,299,284.3
XS GIS Cut Line= 3
     1851007.494      300395.177     1850402.198        300874.2
     1850282.259      301224.877
#Sta/Elev= 30
       0  1761.1    29.7 1756.14   128.6 1734.52   158.3 1733.12   296.9 1715.37
   316.7 1709.99   376.1 1687.53   415.6 1676.75   425.5 1672.82   465.1 1665.15
   534.4 1660.21   548.7 1657.59   563.7 1654.17     574  1653.3   583.9 1653.49
   593.8 1655.56   633.4 1674.47   653.2 1681.94     673 1687.21   722.4  1693.3
   732.3 1693.15   771.9 1698.91   879.2 1704.77     928 1712.86   947.5 1714.64
   976.7 1722.44  1035.2 1732.08  1054.8 1733.63  1132.8 1747.03  1142.5 1747.46
#Mann= 3 , 0 , 0
       0      .1       0   548.7    .045       0   563.7      .1       0
Bank Sta=548.7,563.7
XS Rating Curve= 0 ,0
Exp/Cntr=0.3,0.1

Type RM Length L Ch R = 1 ,5788    ,257.8,250.8,247.2
XS GIS Cut Line= 3
     1850599.609      300028.792      1850395.51      300507.015
     1850223.503      301178.933
#Sta/Elev= 30
       0 1791.98      40 1782.15      60 1774.21      80 1769.41     120 1756.41
     220 1738.81     260 1726.58     270 1726.04     360 1701.06     380 1698.03
     460 1675.42     480 1672.16     490 1667.58   512.5 1654.16     520 1652.01
   527.5 1652.25   569.5  1659.3   648.8 1659.91   678.5 1663.07     728 1683.87
   767.7 1695.83   787.5 1699.04   797.4 1699.87   827.1 1694.95     837 1695.94
   856.8 1703.07   866.8 1704.17   995.6 1709.44  1074.8 1718.26  1213.5  1737.7
#Mann= 3 , 0 , 0
       0      .1       0   512.5    .045       0   527.5      .1       0
Bank Sta=512.5,527.5
XS Rating Curve= 0 ,0
Exp/Cntr=0.3,0.1

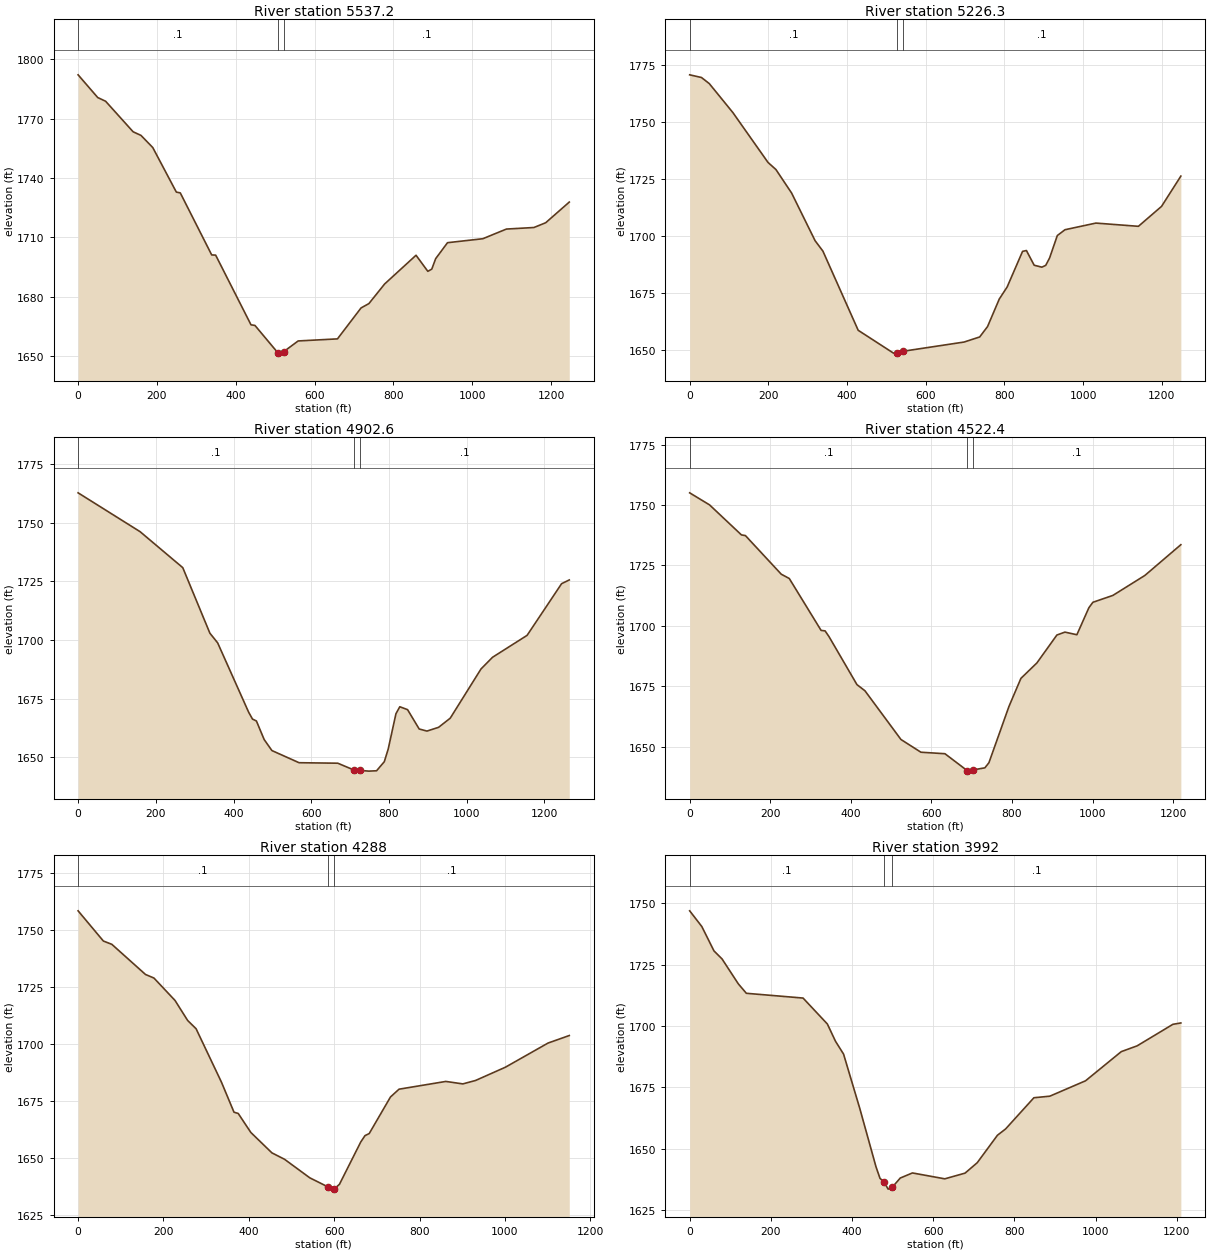
Type RM Length L Ch R = 1 ,5537.2  ,325.6,311,296.4
XS GIS Cut Line= 3
     1850202.989      299920.336     1850131.801      300714.568
     1850145.634      301162.858
#Sta/Elev= 30
       0 1792.11    49.8 1780.63    69.8 1778.76   139.6 1763.33   159.5 1761.51
   189.4 1755.37   249.2 1732.86   259.2 1732.46   338.9 1701.11   348.9 1701.02
   438.6  1665.8   448.6 1665.49   506.5 1651.72   508.4  1651.5   521.5 1652.24
   558.2 1657.65   657.9  1658.7   717.7 1674.32   737.6 1676.52   777.5 1686.43
   857.2 1700.95   887.1 1692.83   897.1 1693.93     907 1699.23     937 1707.29
  1026.6  1709.3  1086.4 1714.18  1156.2 1714.97  1186.1 1717.38  1245.9 1727.82
#Mann= 3 , 0 , 0
       0      .1       0   506.5    .045       0   521.5      .1       0
Bank Sta=506.5,521.5
XS Rating Curve= 0 ,0
Exp/Cntr=0.3,0.1

Type RM Length L Ch R = 1 ,5226.3  ,315.7,323.3,330.6
XS GIS Cut Line= 3
     1849589.083      300066.547     1850027.552      300743.889
     1850074.564      301182.906
#Sta/Elev= 30
       0 1770.77    29.9  1769.6    49.8 1766.93   109.6 1754.24   199.2 1732.28
   219.2 1729.19     259 1718.89   318.8 1697.93   338.7 1693.34   428.3  1658.6
     518 1648.57   526.9  1648.8   541.9 1649.38   697.3 1653.43   737.1 1655.67
   757.1 1660.23     787 1672.35   806.9 1677.61   846.1 1693.25   855.9 1693.62
   875.6 1687.16   895.2 1686.32     905 1687.12   914.8 1690.36   934.4  1700.2
     954 1702.76  1032.5 1705.67  1140.5 1704.25  1199.3    1713  1248.4  1726.3
#Mann= 3 , 0 , 0
       0      .1       0   526.9    .045       0   541.9      .1       0
Bank Sta=526.9,541.9
XS Rating Curve= 0 ,0
Exp/Cntr=0.3,0.1

Type RM Length L Ch R = 1 ,4902.6  ,367.5,380.5,393.8
XS GIS Cut Line= 3
     1849525.068      300095.904     1849779.959      301050.121
     1849999.467      301218.275
#Sta/Elev= 30
       0 1762.78   159.6  1746.2   269.4 1730.85   339.2 1702.89   359.2 1698.76
     439 1669.16   448.9 1666.23   458.9 1665.44   478.9 1657.51   498.8 1652.81
   568.7 1647.62   668.4 1647.41     711 1644.43     726 1644.33   748.2 1644.03
   768.2 1644.18   788.1 1648.05   798.1 1653.41   818.1 1668.53     828  1671.5
     848 1670.26   877.9 1662.01   897.9 1661.12   927.8 1662.72   957.8 1666.62
    1037 1687.62  1066.7 1692.61  1155.6 1701.96  1244.4 1724.01  1264.2 1725.61
#Mann= 3 , 0 , 0
       0      .1       0     711    .045       0     726      .1       0
Bank Sta=711,726
XS Rating Curve= 0 ,0
Exp/Cntr=0.3,0.1

Type RM Length L Ch R = 1 ,4522.4  ,235.5,234.4,238.2
XS GIS Cut Line= 3
      1849451.84      300100.921     1849467.211      300515.843
     1849187.388      301269.583
#Sta/Elev= 30
       0    1755    49.4    1750   128.5 1737.58   138.4  1737.3   227.4 1721.31
   247.2 1719.55   326.2 1698.06   336.1 1697.86     346 1695.44   415.2 1675.62
   435.1 1673.06   524.4 1652.91     574 1647.63   633.6 1647.02   689.2 1639.98
   693.1 1639.81   704.2 1640.33   732.8 1641.18   742.8 1643.29   792.4 1666.53
   822.2  1678.2   861.9  1684.6   911.5 1696.14   931.4 1697.35   961.1 1696.26
   990.9 1707.43  1000.8 1709.69  1050.5 1712.54  1129.9  1720.8  1219.2 1733.53
#Mann= 3 , 0 , 0
       0      .1       0   689.2    .045       0   704.2      .1       0
Bank Sta=689.2,704.2
XS Rating Curve= 0 ,0
Exp/Cntr=0.3,0.1

Type RM Length L Ch R = 1 ,4288    ,308.4,295.9,278.6
XS GIS Cut Line= 3
     1849381.437      300071.297     1849189.964      300631.717
     1848907.487      301113.385
#Sta/Elev= 30
       0 1758.33    59.2 1745.08      79 1743.64   157.9 1730.41   177.7 1728.84
     227 1719.03   256.6 1710.24   276.4  1706.6   335.6 1683.26   365.2 1669.99
   375.1 1669.44   404.7  1661.1     454 1652.16   483.6 1649.34   542.9 1641.19
   584.7 1637.28   592.2 1636.25   599.7  1636.3   612.2 1638.36     662 1656.89
     672 1659.71     682 1660.64   731.8 1676.68   751.8 1680.09   861.4 1683.49
   901.3 1682.41   931.2 1683.92    1001 1689.73  1100.8 1700.32  1150.6 1703.63
#Mann= 3 , 0 , 0
       0      .1       0   584.7    .045       0   599.7      .1       0
Bank Sta=584.7,599.7
XS Rating Curve= 0 ,0
Exp/Cntr=0.3,0.1

Type RM Length L Ch R = 1 ,3992    ,304.1,303.9,305.7
XS GIS Cut Line= 3
     1848829.489      299954.883     1849027.408      300779.724
     1848830.385      301083.423
#Sta/Elev= 30
       0 1746.97    29.9 1740.57    59.9 1730.62    79.8 1727.34   119.8  1717.2
   139.7 1713.33   279.4 1711.39   339.3 1700.81   359.3 1693.78   379.2 1688.53
   419.1 1666.41   459.1 1642.58     469 1637.85     479 1636.38     489 1633.46
     499 1634.19   518.9 1637.98   548.9 1640.06   628.7 1637.66   678.6 1639.99
   708.5 1644.22   758.4 1655.44   778.4 1657.99   848.2 1670.73   887.4 1671.37
   975.4 1677.64  1063.5 1689.54  1102.6  1691.9  1190.7 1700.68  1210.3 1701.24
#Mann= 3 , 0 , 0
       0      .1       0     479    .045       0     499      .1       0
Bank Sta=479,499
XS Rating Curve= 0 ,0
Exp/Cntr=0.3,0.1

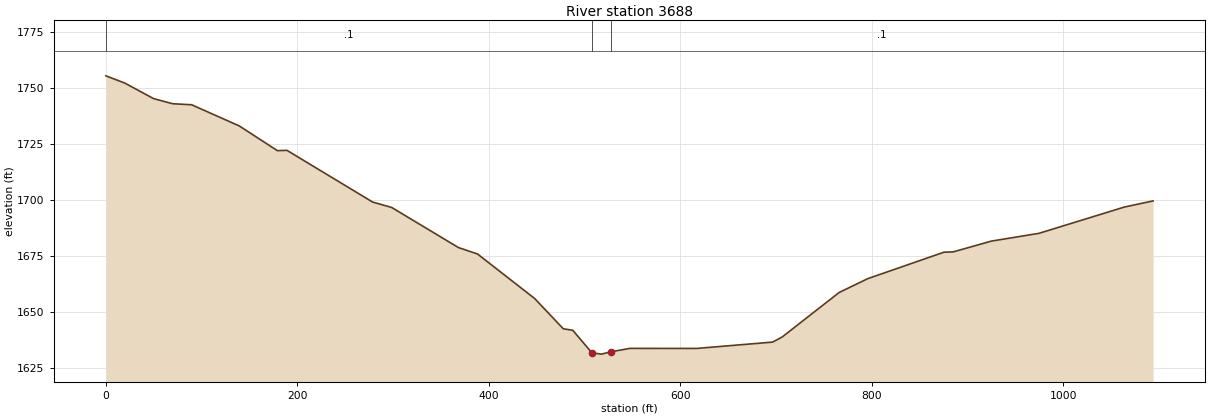
Type RM Length L Ch R = 1 ,3688    ,307.6,316.6,323.7
XS GIS Cut Line= 3
     1848529.417       300023.84     1848662.302      300554.795
     1848746.596      301094.531
#Sta/Elev= 30
       0 1755.28    19.9 1752.02    49.8 1745.13    69.7 1742.85    89.6 1742.38
   139.3 1732.95   179.1 1721.94   189.1 1722.08   278.6 1699.03   298.5 1696.62
   368.2 1678.76   388.1  1675.9   447.8 1656.05   477.7 1642.57   487.6 1641.91
   507.5 1631.88   517.5 1631.28   527.4 1632.32   547.3 1633.84   616.9 1633.81
   696.3 1636.64   706.2 1638.89   765.8 1658.75   795.6  1664.9   875.1 1676.68
     885 1676.85   924.8 1681.64   974.4 1685.09  1063.8 1696.83  1093.6 1699.54
#Mann= 3 , 0 , 0
       0      .1       0   507.5    .045       0   527.4      .1       0
Bank Sta=507.5,527.4
XS Rating Curve= 0 ,0
Exp/Cntr=0.3,0.1