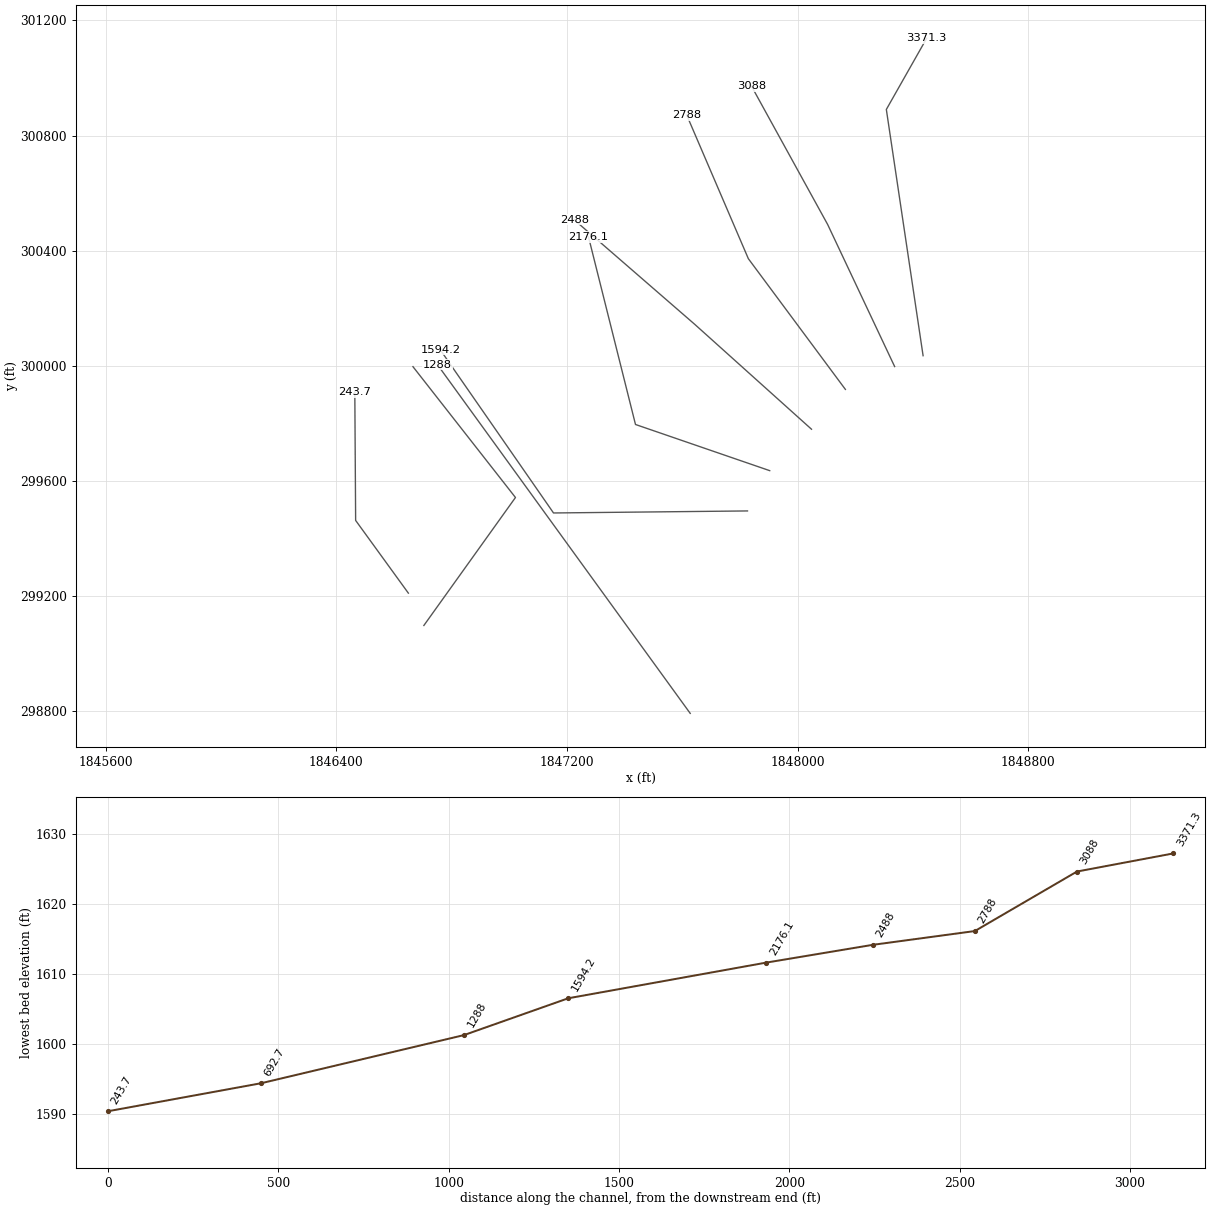
HEC-RAS study SndlckCrk.prj: SndlckCrk

--- SndlckCrk.g01 (geometry) --- (continued)

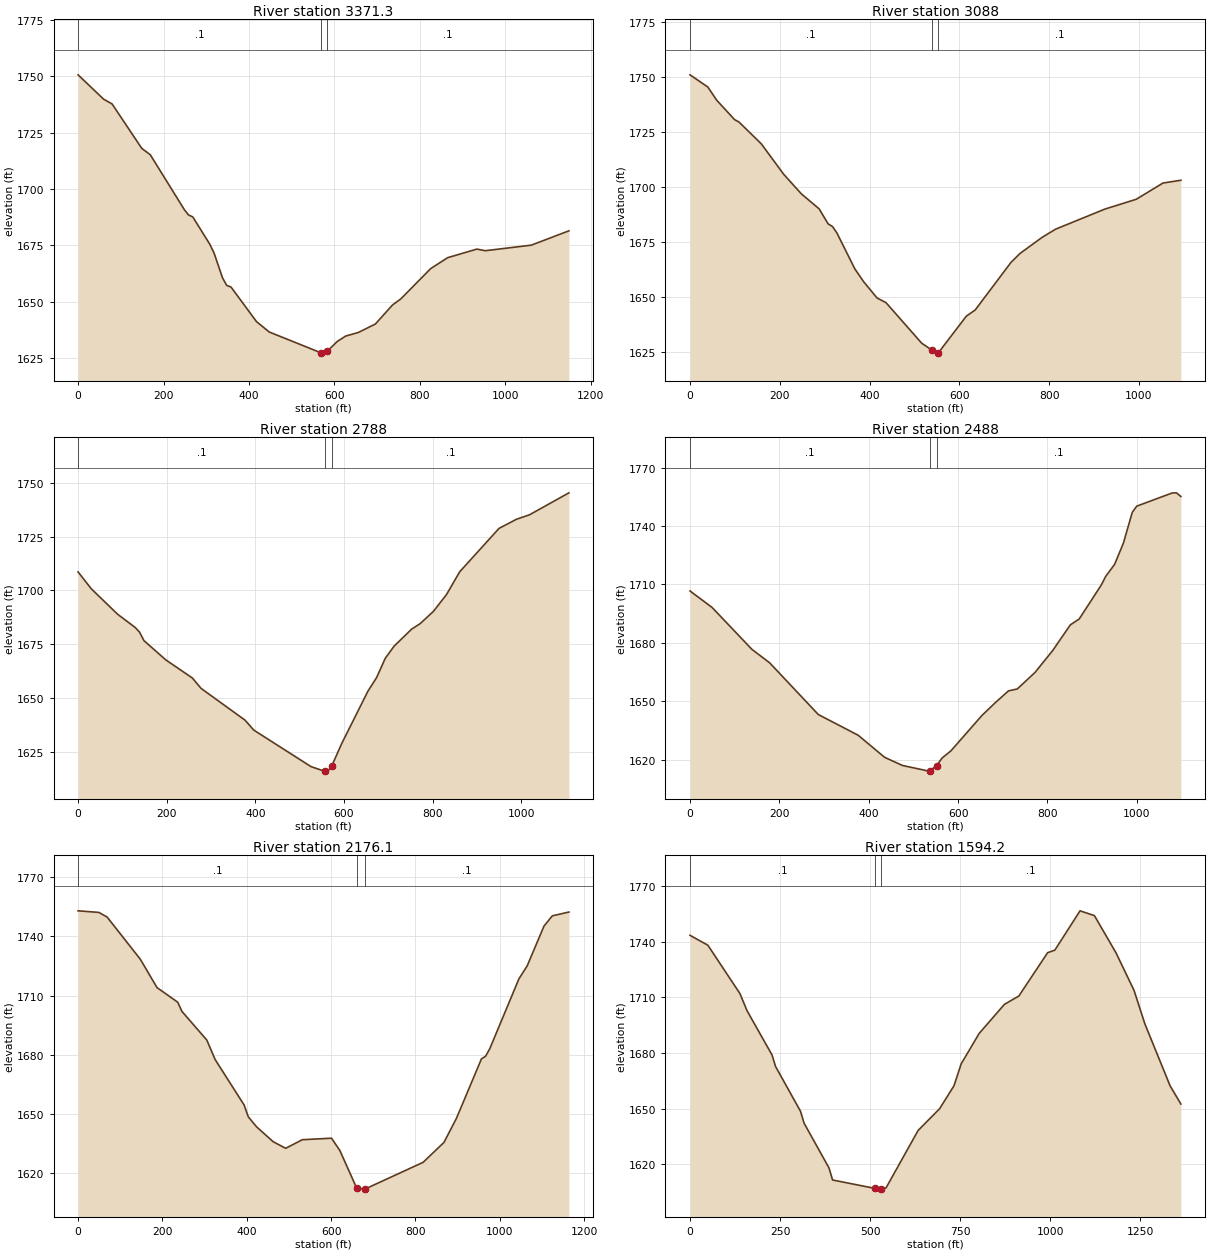
Type RM Length L Ch R = 1 ,3371.3  ,276.7,283.2,291.1
XS GIS Cut Line= 3
     1848434.908      300034.837     1848307.436      300890.489
     1848447.208      301137.635
#Sta/Elev= 30
       0 1750.67    59.7 1739.88    79.6 1737.75   149.2 1718.02     169 1715.22
   248.6  1690.9   258.5 1688.51   268.5 1687.63   308.2 1675.56   318.2 1671.68
   338.1 1660.61     348 1657.23     358 1656.53   417.6  1641.2   447.5 1636.58
   568.6 1627.35   576.7 1627.21   583.6 1628.11   606.6 1632.37   626.4 1634.78
   656.3 1636.39     696 1640.14   735.8 1648.52   755.7 1651.31   825.3 1664.69
   865.1 1669.56   933.6 1673.36   953.2 1672.64  1060.9 1675.11    1149 1681.47
#Mann= 3 , 0 , 0
       0      .1       0   568.6    .045       0   583.6      .1       0
Bank Sta=568.6,583.6
XS Rating Curve= 0 ,0
Exp/Cntr=0.3,0.1

Type RM Length L Ch R = 1 ,3088    ,295.4,299.9,297.8
XS GIS Cut Line= 3
     1848336.234      299997.144       1848103.9      300490.902
     1847840.099      300970.953
#Sta/Elev= 30
       0 1750.97    39.7 1745.43    59.5 1739.44    99.2 1730.64   109.1 1729.54
   158.8 1719.64   208.4 1705.89     248 1696.93   287.7 1690.11   307.6 1683.31
   317.5 1682.08   327.4 1679.11   367.1 1662.89   386.9    1657   416.7 1649.65
   436.6 1647.54   515.9 1629.17   538.2 1626.06   545.7 1624.62   553.2 1624.76
   615.4 1641.38   635.3 1644.22     715 1665.82   734.9 1669.84   784.7 1677.24
   814.6 1680.92   924.1 1690.01   993.9 1694.46  1053.6 1701.84  1093.4 1703.12
#Mann= 3 , 0 , 0
       0      .1       0   538.2    .045       0   553.2      .1       0
Bank Sta=538.2,553.2
XS Rating Curve= 0 ,0
Exp/Cntr=0.3,0.1

Type RM Length L Ch R = 1 ,2788    ,295.5,300,310.1
XS GIS Cut Line= 3
     1848165.426      299917.787     1847828.971      300371.956
     1847615.326      300870.735
#Sta/Elev= 30
       0 1708.59    29.8 1700.77    89.2 1688.96   128.9 1682.81   138.8 1680.61
   148.7  1676.7   198.3 1667.71   257.8 1659.38   277.6 1654.53   376.8 1639.78
   396.6 1635.16   525.6 1618.23   555.3 1616.12   557.7 1616.22   565.2 1616.54
   572.7 1618.59   594.8 1628.86     654 1653.17   673.7 1659.55   693.5 1668.58
   713.2 1674.12   752.7 1682.02   772.4 1684.66     802  1690.3   831.6 1698.13
   861.2 1708.65     950 1728.81   989.4 1733.05    1019 1735.14  1107.8 1745.32
#Mann= 3 , 0 , 0
       0      .1       0   557.7    .045       0   572.7      .1       0
Bank Sta=557.7,572.7
XS Rating Curve= 0 ,0
Exp/Cntr=0.3,0.1

Type RM Length L Ch R = 1 ,2488    ,325.2,311.8,298.1
XS GIS Cut Line= 3
     1848047.939      299779.427     1847643.194      300143.738
     1847224.941      300507.312
#Sta/Elev= 30
       0 1706.68    49.5 1698.19   138.6 1676.68   178.2 1669.78   287.1 1643.23
   376.2  1632.6   435.6 1621.24   475.2 1617.08   534.6 1614.15   537.1 1614.37
   552.1    1617   564.4 1620.92   584.1 1624.59   653.4 1642.73   683.1 1649.26
   712.8 1655.36   732.6 1656.35   772.2 1664.83   811.8 1676.08   851.3 1689.27
   871.1 1692.28   920.6 1709.75   930.5 1714.19   950.3  1720.3   970.1 1731.28
   989.9 1747.05   999.8 1750.22    1079 1756.99  1088.8 1757.08  1098.7  1755.2
#Mann= 3 , 0 , 0
       0      .1       0   537.1    .045       0   552.1      .1       0
Bank Sta=537.1,552.1
XS Rating Curve= 0 ,0
Exp/Cntr=0.3,0.1

Type RM Length L Ch R = 1 ,2176.1  ,551.8,581.8,611.8
XS GIS Cut Line= 3
     1847902.996      299635.463     1847437.604       299795.87
     1847274.715      300447.429
#Sta/Elev= 30
       0 1753.03    49.2 1752.23    68.9 1749.87   147.7  1728.4   187.1 1714.04
   236.3 1706.59   246.1 1701.97   305.2 1687.38   324.9  1677.5   393.8 1654.33
   403.6 1648.37   423.3 1643.26   462.7  1635.7   492.3 1632.37   531.8 1636.73
   600.9  1637.5   620.7 1631.25   660.2 1612.35   679.9 1611.62   818.2 1625.24
   867.6 1635.37   897.2 1647.61   956.5 1677.82   966.3 1679.14   976.2 1682.98
  1045.4  1718.5  1065.1 1725.15  1104.6 1745.21  1124.4 1750.47  1163.9 1752.42
#Mann= 3 , 0 , 0
       0      .1       0   660.2    .045       0   679.9      .1       0
Bank Sta=660.2,679.9
XS Rating Curve= 0 ,0
Exp/Cntr=0.3,0.1

Type RM Length L Ch R = 1 ,1594.2  ,329,306.2,280
XS GIS Cut Line= 3
     1847825.996      299495.479     1847153.362      299488.416
     1846760.711      300055.387
#Sta/Elev= 30
       0 1743.43    49.5  1738.1   138.5 1712.04   158.3 1702.76   227.5 1678.93
   237.4 1672.69   306.7  1648.5   316.6  1642.1   385.8 1617.92   395.7 1611.45
   513.9 1606.89   528.9 1606.56   534.2 1606.52   544.1 1607.21   633.1 1638.18
   692.7 1649.88   732.6 1662.27   752.6 1674.12   802.6 1690.52   872.6 1706.19
   912.6 1710.68   992.5 1734.05  1012.5 1735.43  1082.5 1756.64  1122.4 1754.05
  1182.4 1733.94  1232.4 1713.69  1262.4 1695.67  1332.4 1662.25  1362.3 1652.43
#Mann= 3 , 0 , 0
       0      .1       0   513.9    .045       0   528.9      .1       0
Bank Sta=513.9,528.9
XS Rating Curve= 0 ,0
Exp/Cntr=0.3,0.1

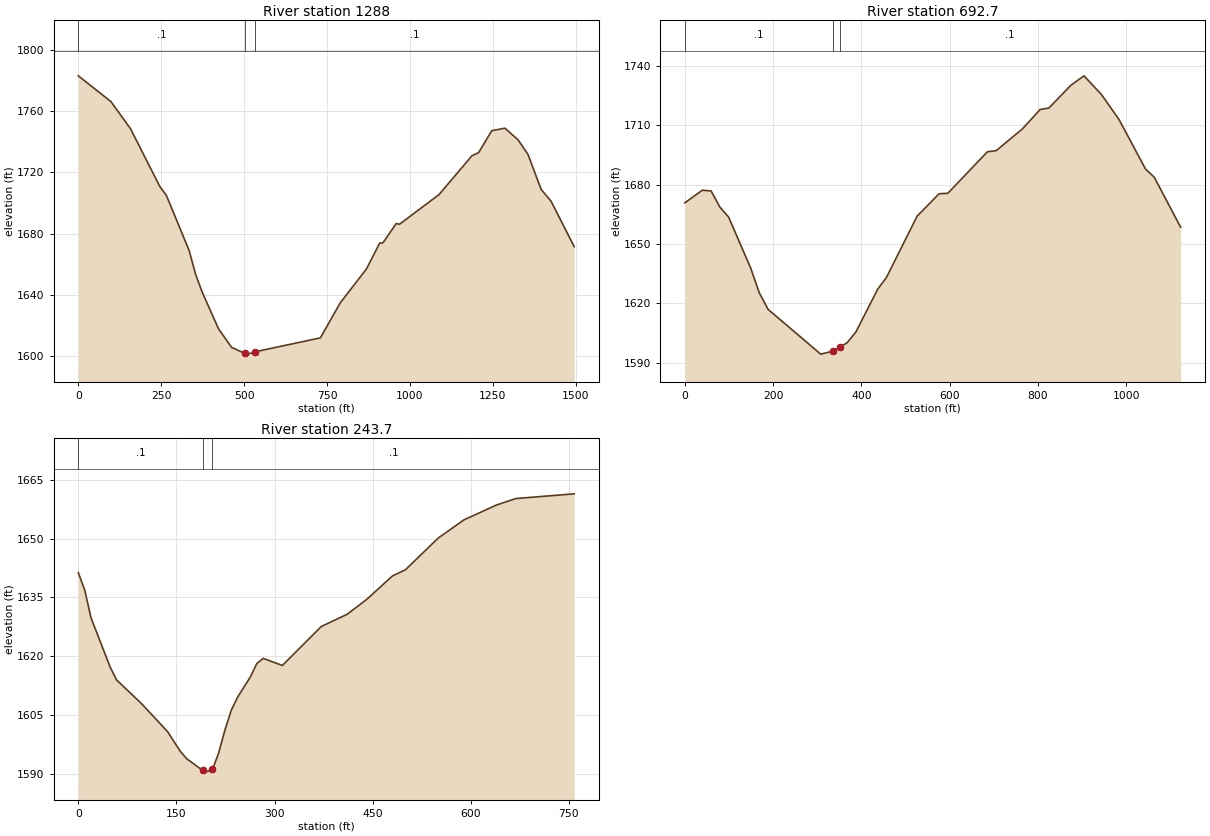
Type RM Length L Ch R = 1 ,1288    ,623.2,595.2,570.6
XS GIS Cut Line= 3
     1847627.371      298792.062     1847339.298      299190.243
     1846751.226       300003.26
#Sta/Elev= 30
       0 1782.95    98.3 1766.14   157.3 1748.43   245.7 1710.69   265.4 1704.94
   334.2 1668.84   353.8 1653.17   373.5  1641.7   422.7  1617.8     462 1605.71
   501.4 1601.78   511.3 1601.26   531.2 1602.71   729.9 1611.88   789.5 1634.67
     869 1656.96   908.7 1673.79   918.6 1673.95   958.4 1686.51   968.3 1686.05
  1087.5 1705.42  1186.9  1730.8  1206.8 1732.78  1246.5 1747.14  1286.2 1748.77
    1326 1741.12  1355.8 1731.61  1395.5 1708.75  1425.3 1701.07  1494.9 1671.49
#Mann= 3 , 0 , 0
       0      .1       0   501.4    .045       0   531.2      .1       0
Bank Sta=501.4,531.2
XS Rating Curve= 0 ,0
Exp/Cntr=0.3,0.1

Type RM Length L Ch R = 1 ,692.7   ,420.9,449.6,478.2
XS GIS Cut Line= 3
     1846703.786       299097.48     1847021.421      299542.169
     1846665.971      299996.774
#Sta/Elev= 30
       0 1670.84    39.7 1677.19    59.6 1676.86    79.5 1668.67    99.4  1663.6
     149 1638.04   168.9 1625.31   188.8 1617.01     308 1594.39   335.8  1595.9
   350.8  1597.8   367.6  1600.1   387.5 1605.48   437.2 1627.23   457.1 1633.17
   526.6 1664.13   576.3 1675.42   596.2 1675.68   685.8 1696.64   705.7 1697.19
   765.4 1708.26   805.2 1717.98   825.1 1718.73   874.8 1730.22   904.7    1735
   944.5 1725.47   984.3 1712.81    1044 1687.94  1063.8  1683.8  1123.6 1658.53
#Mann= 3 , 0 , 0
       0      .1       0   335.8    .045       0   350.8      .1       0
Bank Sta=335.8,350.8
XS Rating Curve= 0 ,0
Exp/Cntr=0.3,0.1

Type RM Length L Ch R = 1 ,243.7   ,268.8,243.1,217.3
XS GIS Cut Line= 3
     1846650.032      299209.874     1846467.199      299462.516
     1846464.338      299908.671
#Sta/Elev= 30
       0 1641.32     9.8 1636.85    19.5 1629.74    48.7 1617.19    58.5 1613.94
    97.5 1607.74   136.4 1600.73   155.9 1595.71   165.7  1593.8   190.1 1590.83
   194.9 1590.39   205.1 1591.11   214.4 1595.19   224.2  1601.2   233.9 1606.23
   243.6 1609.56   263.1 1614.73   272.9 1618.13   282.6 1619.44   311.9 1617.63
   371.4 1627.58     411  1630.7   440.8 1634.49   480.4 1640.51   500.2 1642.08
   549.8 1650.11   589.5 1654.81     639 1658.58   668.8 1660.25     758 1661.46
#Mann= 3 , 0 , 0
       0      .1       0   190.1    .045       0   205.1      .1       0
Bank Sta=190.1,205.1
XS Rating Curve= 0 ,0
Exp/Cntr=0.3,0.1

Chan Stop Cuts=-1
Use User Specified Reach Order=0
Composite Channel Slope=5